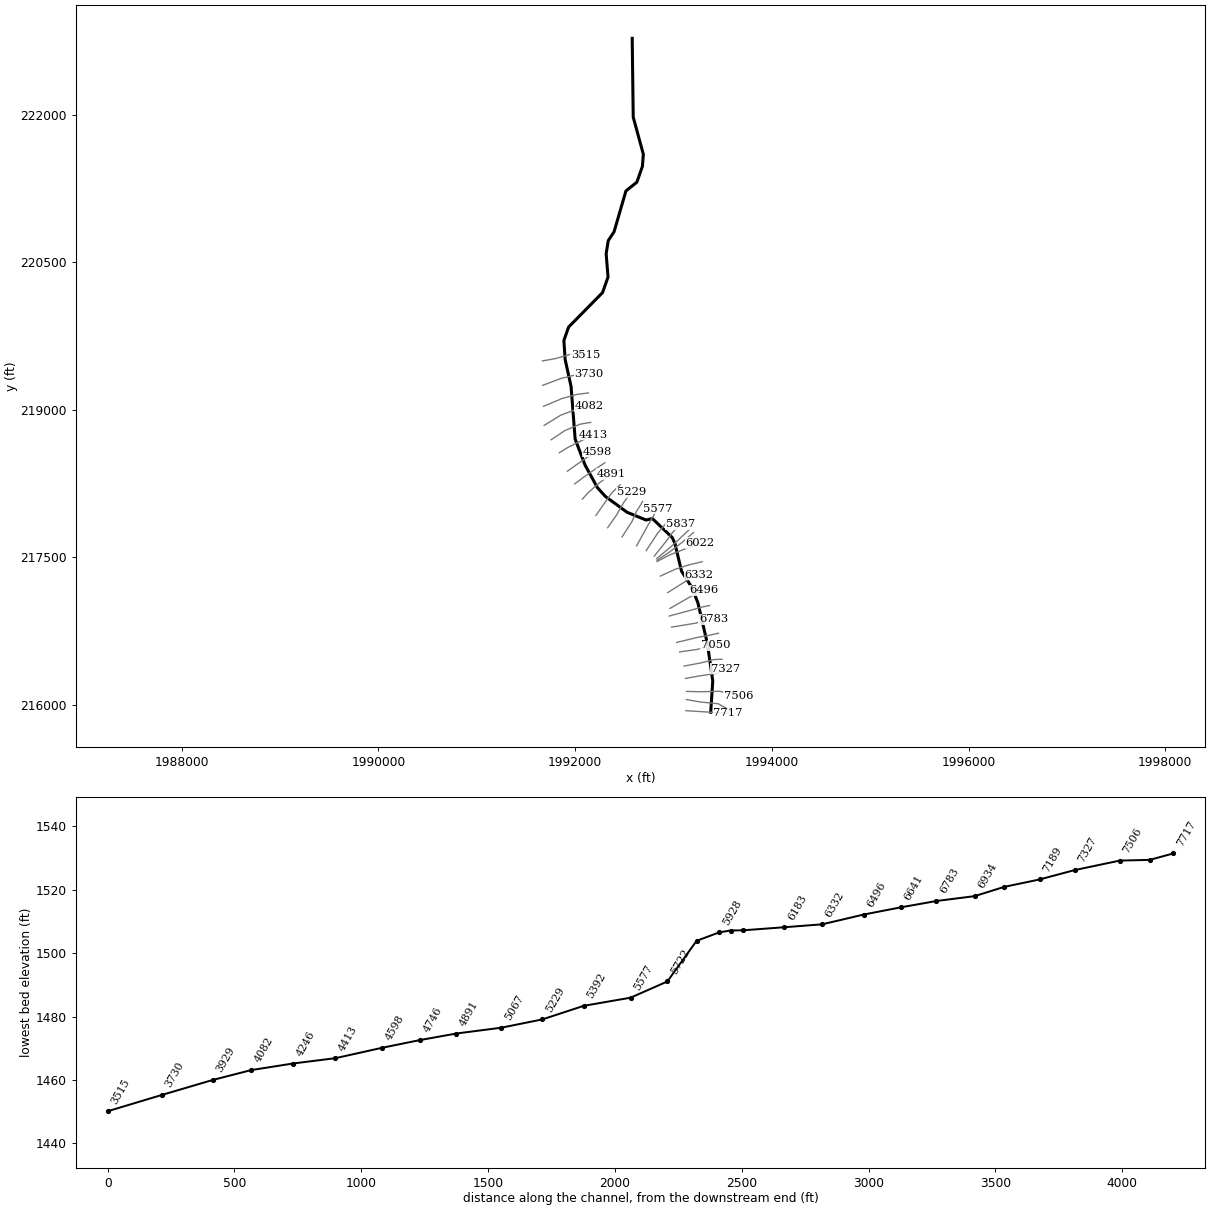
--- PIPESTCK1_A.prj (project) ---

Proj Title=PIPESTCK1_A
Current Plan=p01
Default Exp/Contr=0,0
English Units
Geom File=g01
Flow File=f01
Plan File=p01
BEGIN DESCRIPTION:
Stream Name: Pipestem Creek
Flood Zone: Approximate
Summers County, West Virginia
HEC-RAS Version: 5.0.7
Hydrology Method:
Regression.
Model Notes:
END DESCRIPTION:
DSS Export Rating Curves= 0
DSS Export Rating Curve Sorted= 0
DSS Export Volume Flow Curves= 0
DXF OffsetX= 0
DXF OffsetY= 0
DXF ScaleX= 0
DXF ScaleY= 0

--- PIPESTCK1_A.p01 (plan) ---

Plan Title=Floodplain
Program Version=5.07
Short Identifier=Floodplain
Geom File=g01
Flow File=f01
Subcritical Flow
K Sum by GR= 0
Std Step Tol= 0.01
Critical Tol= 0.01
Num of Std Step Trials= 20
Max Error Tol= 0.3
Flow Tol Ratio= 0.001
Split Flow NTrial= 30
Split Flow Tol= 0.02
Split Flow Ratio= 0.02
Log Output Level= 0
Friction Slope Method= 1
Unsteady Friction Slope Method= 2
Unsteady Bridges Friction Slope Method= 1
Parabolic Critical Depth
Global Vel Dist= 0 , 0 , 0
Global Log Level= 0
CheckData=True
Encroach Param=-1 ,0,0, 0
Mapping Interval=1HOUR
Computation Time Step Use Courant=        0
Computation Time Step Use Time Series=    0
Computation Time Step Count To Double=0
Computation Time Step Max Doubling=0
Computation Time Step Max Halving=0
Computation Time Step Residence Courant=0
Run HTab= 0
Run UNet= 0
Run Sediment= 0
Run PostProcess= 0
Run WQNet= 0
Run RASMapper= 0
UNET Theta= 0
UNET Theta Warmup= 0
UNET ZTol= 0
UNET ZSATol= 0
UNET MxIter= 0
UNET Max Iter WO Improvement= 0
UNET MaxInSteps= 0
UNET DtIC= 0
UNET DtMin= 0
UNET MaxCRTS= 0
UNET WFStab= 0
UNET SFStab= 0
UNET WFX= 1
UNET SFX= 1
UNET 1D Methodology=Finite Difference
UNET DSS MLevel= 1
UNET Pardiso=0
UNET DZMax Abort= 0
UNET Use Existing IB Tables= 0
UNET Froude Reduction=False
UNET Froude Limit= 0
UNET Froude Power= 0
UNET D1 Cores= 0
UNET D2 Coriolis=0
UNET D2 Cores= 0
UNET D2 Theta= 1
UNET D2 Theta Warmup= 1
UNET D2 Z Tol= 0.01
UNET D2 Volume Tol= 0.01
UNET D2 Max Iterations= 20
UNET D2 Equation= 0
UNET D2 RampUpFraction=0.1
UNET D2 TimeSlices= 1
UNET D2 Eddy Viscosity=0.3
UNET D2 BCVolumeCheck=0
UNET D1D2 MaxIter= 0
UNET D1D2 ZTol=0.01
UNET D1D2 QTol=0.1
UNET D1D2 MinQTol=1
Write IC File= 0
Write IC File at Fixed DateTime=0
Write IC File at Sim End=0
Echo Input=False
Echo Parameters=False
Echo Output=False
Write Detailed= 0
HDF Write Warmup=0
HDF Write Time Slices=0
HDF Flush=0
HDF Face Node Velocities=0
HDF Compression= 1
HDF Chunk Size= 1
HDF Spatial Parts= 1
HDF Use Max Rows=0
HDF Fixed Rows= 1
Calibration Method= 0
Calibration Iterations= 20
Calibration Max Change=0.05
Calibration Tolerance=0.2
Calibration Maximum=1.5
Calibration Minimum=0.5
Calibration Optimization Method= 1
WQ AD Non Conservative
WQ ULTIMATE=-1
WQ Max Comp Step=1HOUR
WQ Output Interval=15MIN
WQ Output Selected Increments= 0
WQ Output face flow=0
WQ Output face velocity=0
WQ Output face area=0
WQ Output face dispersion=0
WQ Output cell volume=0
WQ Output cell surface area=0
WQ Output cell continuity=0
WQ Output cumulative cell continuity=0
WQ Output face conc=0
WQ Output face dconc_dx=0
WQ Output face courant=0
WQ Output face peclet=0
WQ Output face adv mass=0
WQ Output face disp mass=0
WQ Output cell mass=0
WQ Output cell source sink temp=0
WQ Output nsm pathways=0
WQ Output nsm derived pathways=0
WQ Output MaxMinRange=-1
WQ Daily Max Min Mean=-1
WQ Daily Range=0
WQ Daily Time=0
WQ Create Restart=0
WQ Fixed Restart=0
WQ System Summary=0
WQ Write To DSS=0
WQ Use Fixed Temperature=0
Sorting and Armoring Iterations= 10
XS Update Threshold= 0.02
Bed Roughness Predictor= 0
Hydraulics Update Threshold= 0.02
Energy Slope Method= 1
Volume Change Method= 1
Sediment Retention Method= 0
XS Weighting Method= 0
Number of US Weighted Cross Sections= 1
Number of DS Weighted Cross Sections= 1
Upstream XS Weight=0
Main XS Weight=1
Downstream XS Weight=0
Number of DS XS's Weighted with US Boundary= 1
Upstream Boundary Weight= 1
Weight of XSs Associated with US Boundary= 0
Number of US XS's Weighted with DS Boundary= 1
Downstream Boundary Weight= 0.5
Weight of XSs Associated with DS Boundary= 0.5
Percentile Method= 0
Sediment Output Level= 3
Mass or Volume Output= 0
Output Increment Type= 1
Profile and TS Output Increment= 1
XS Output Flag= 0
XS Output Increment= 10
Write Gradation File= 0
Read Gradation Hotstart= 0
Write HDF5 File= 1
Write Binary Output= 1
Write DSS Sediment File= 0
SV Curve= 0
Specific Gage Flag= 0

--- PIPESTCK1_A.f01 (steady flow) ---

Flow Title=Flows
Program Version=5.07
Number of Profiles= 6
Profile Names=01pct,10pct,04pct,02pct,0_2pct,01plus
River Rch & RM=PIPESTCK1_A,Main            ,7717
    2503    1401    1812    2147    3401    3702
Boundary for River Rch & Prof#=PIPESTCK1_A,Main            , 1
Up Type= 0
Dn Type= 3
Dn Slope=0.00018
Boundary for River Rch & Prof#=PIPESTCK1_A,Main            , 2
Up Type= 0
Dn Type= 3
Dn Slope=0.00018
Boundary for River Rch & Prof#=PIPESTCK1_A,Main            , 3
Up Type= 0
Dn Type= 3
Dn Slope=0.00018
Boundary for River Rch & Prof#=PIPESTCK1_A,Main            , 4
Up Type= 0
Dn Type= 3
Dn Slope=0.00018
Boundary for River Rch & Prof#=PIPESTCK1_A,Main            , 5
Up Type= 0
Dn Type= 3
Dn Slope=0.00018
Boundary for River Rch & Prof#=PIPESTCK1_A,Main            , 6
Up Type= 0
Dn Type= 3
Dn Slope=0.00018
DSS Import GetInterval= 0
DSS Import GetPeak= 0
DSS Import FillOption= 0

--- PIPESTCK1_A.g01 (geometry) ---

Geom Title=Geometry
Program Version=5.07

River Reach=PIPESTCK1_A     ,Main
Reach XY= 30
1993378.29953525215925.0424859211993399.22900003216242.609000013
     1993344.541216622.8180000141993248.18699999217038.182000028
1993185.68700002217195.734000044     1993081.521217359.796999981
1993013.81200002217643.650999981     1992986.469217702.245000041
     1992785.948217893.650999998     1992720.844 217879.32799999
1992529.43700002217957.4530000211992308.08300002218118.478000011
1992225.61800002218209.622999984      1992101.92218436.186000031
1992000.35700002218701.8110000261991958.69099999219238.268999991
1991898.52600001 219511.728000051991885.77400002219704.415000006
1991933.63600002219840.5200000141992279.00400001220191.394000037
1992334.55899999220349.3800000461992315.45889725220585.979896559
1992336.91855541220719.6440000321992396.26835516220810.129940532
1992516.57726918 221224.911179561992627.42700568221313.327040826
1992684.17151365  221474.32308671992693.51729217221597.421437538
1992590.71785083221975.1073533731992580.29400001 222775.99599999

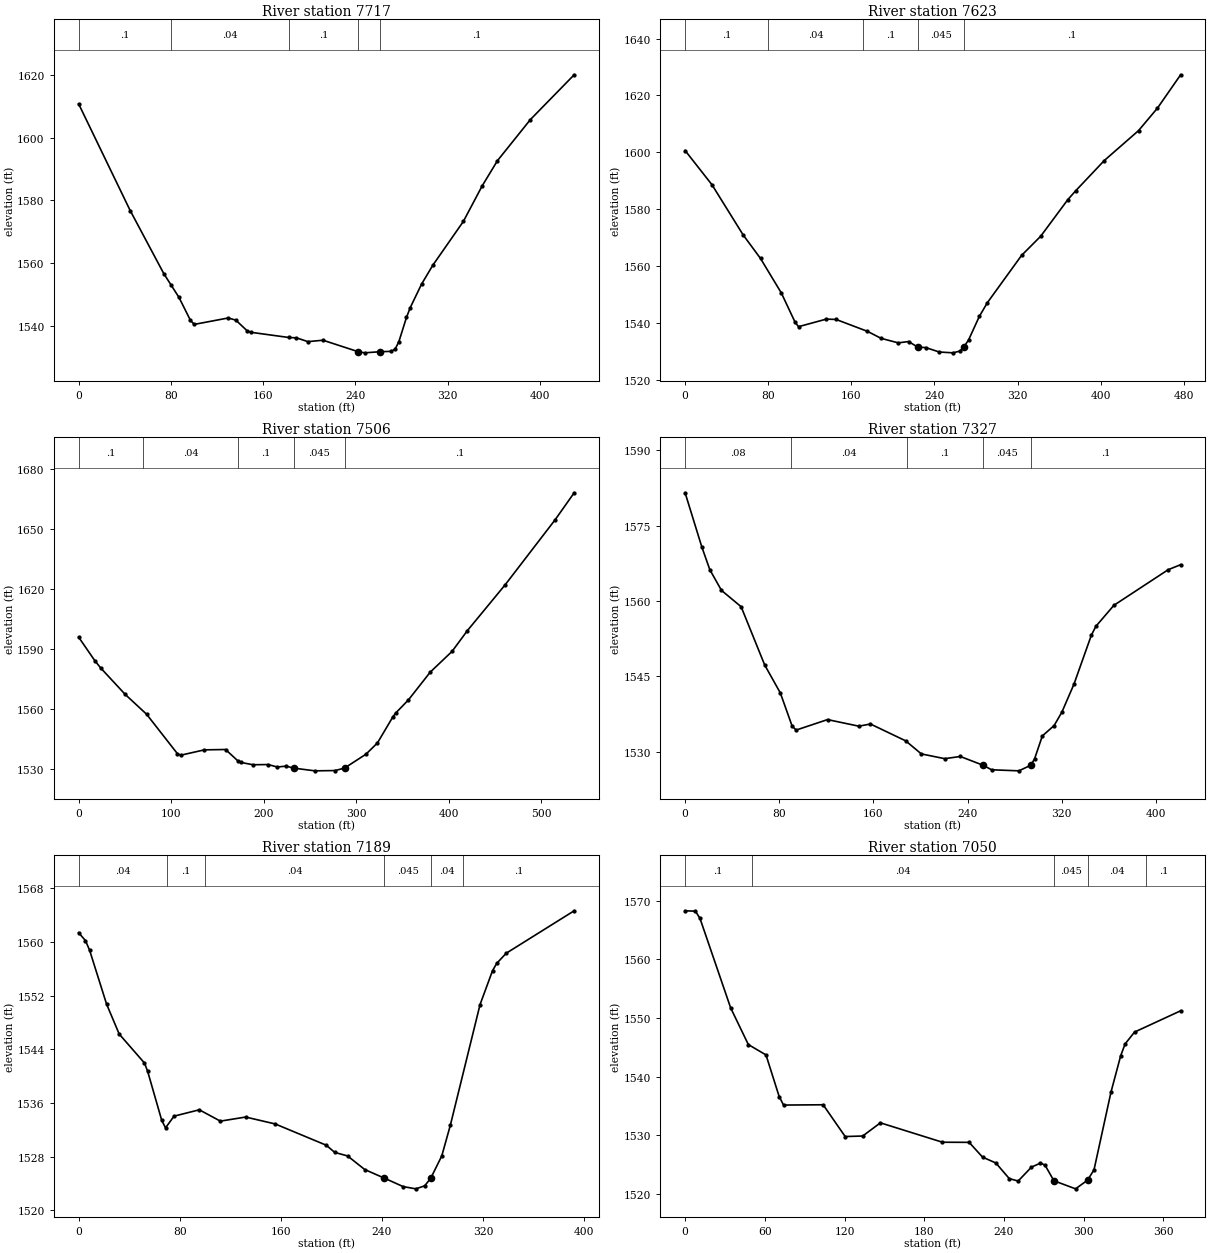
Type RM Length L Ch R = 1 ,7717    ,96.3,93.9,93.3
XS GIS Cut Line= 2
1993125.34377664215941.4282840491993554.16322106215913.650506273
#Sta/Elev= 30
       0 1610.79    44.7 1576.79    73.9 1556.65    80.4 1552.92      87 1549.12
    96.9 1541.84   100.2  1540.5   129.7 1542.55   136.3 1541.87   146.2 1538.44
   149.5 1537.98   182.3 1536.33   188.9 1536.22   198.8 1535.01   211.9 1535.46
   242.3 1531.82   248.1 1531.44   261.3  1531.8   271.1 1531.91   274.4 1532.58
   277.7    1535   284.3 1542.73   287.6 1545.88   297.4 1553.35   307.1 1559.34
   333.6 1573.31     350 1584.69   363.2 1592.69   391.8  1605.8429.7182 1620.06
#Mann= 5 ,-1 , 0
       0      .1       0    80.4     .04       0   182.3      .1       0
   242.3    .045       0   261.3      .1       0
Bank Sta=242.3,261.3
XS Rating Curve= 0 ,0
Exp/Cntr(USF)=0,0
Exp/Cntr=0.3,0.1

Type RM Length L Ch R = 1 ,7623    ,113.4,117.9,123.3
XS GIS Cut Line= 4
1993130.84685249216054.3620086631993270.40767235216029.816135823
1993454.15106332216011.5820588561993585.99746601215938.645750988
#Sta/Elev= 30
       0 1600.63    25.9 1588.56    55.9  1570.9    72.6 1562.62    92.6  1550.5
   105.9 1540.15   109.2 1538.61   135.9 1541.27   145.3 1541.16   175.5 1536.97
   188.7  1534.5   205.2 1532.91   215.1 1533.38  224.241531.354   231.5 1531.27
   244.7 1529.69   257.9  1529.4   264.5 1530.02  268.071531.354   272.8 1533.89
   283.2  1542.2   290.9 1547.03   323.9 1563.71   342.3 1570.45   368.5 1583.38
   376.1  1586.5   403.5  1597.1   436.5 1607.64   454.7 1615.56     477 1627.29
#Mann= 5 ,-1 , 0
       0      .1       0      80     .04       0   171.7      .1       0
  224.24    .045       0  268.07      .1       0
Bank Sta=224.24,268.07
XS Rating Curve= 0 ,0
Exp/Cntr(USF)=0,0
Exp/Cntr=0.3,0.1

Type RM Length L Ch R = 1 ,7506    ,175,178.2,182
XS GIS Cut Line= 4
1993132.21256083216137.0584695551993274.73365062 216133.49544231
1993469.51247333216138.2461453031993661.91594454216091.926791122
#Sta/Elev= 30
       0 1595.91    17.6 1584.09    24.2 1580.33    50.4 1567.28    73.4 1557.43
   106.8 1537.68   110.2 1536.97   135.8 1539.64   158.7 1539.82   171.9  1534.2
   175.2 1533.38   188.3 1532.21   204.7 1532.31   214.5 1531.09   224.4 1531.52
  232.171530.536   255.2 1529.17   276.9 1529.31  287.211530.537   310.4 1537.48
   322.8 1543.11   339.3 1555.99   342.7 1558.12   356.2 1564.55   379.9 1578.48
   403.4  1588.8   419.9 1599.14   460.8 1622.07   514.8 1654.55   535.3 1667.98
#Mann= 5 ,-1 , 0
       0      .1       0      70     .04       0  172.57      .1       0
  232.17    .045       0  287.21      .1       0
Bank Sta=232.17,287.21
XS Rating Curve= 0 ,0
Exp/Cntr(USF)=0,0
Exp/Cntr=0.3,0.1

Type RM Length L Ch R = 1 ,7327    ,134.8,138,140.8
XS GIS Cut Line= 4
1993122.71115484216268.8904776091993259.29386589216293.831668322
1993449.32198561 216322.335886281993526.52090924216368.655240461
#Sta/Elev= 30
       0 1581.52    14.2 1570.74      21 1566.21    30.9 1562.09    47.6 1558.84
    67.6 1547.25    80.9 1541.68    90.9  1535.1    94.3 1534.28     121 1536.37
   147.6 1535.06   157.5 1535.49   187.4 1532.14   200.7 1529.54   220.6 1528.59
   233.8 1529.03  253.261527.276   260.4 1526.38   283.6 1526.17  293.621527.278
   296.9 1528.55   303.5 1533.12   313.5 1535.18   320.1 1537.85   330.3 1543.38
   345.2  1553.2     349 1554.94   364.3 1559.12   410.3 1566.19     421 1567.21
#Mann= 5 ,-1 , 0
       0     .08       0      90     .04       0  188.84      .1       0
  253.26    .045       0  293.62      .1       0
Bank Sta=253.26,293.62
XS Rating Curve= 0 ,0
Exp/Cntr(USF)=0,0
Exp/Cntr=0.3,0.1

Type RM Length L Ch R = 1 ,7189    ,142,139.4,138.5
XS GIS Cut Line= 4
1993108.45904586216394.7841069221993279.48435361216426.851352124
1993413.69171316216461.2939488231993493.26598829 216463.66930032
#Sta/Elev= 30
       0 1561.39     5.4 1560.22     8.7 1558.77    22.1 1550.76    32.1 1546.29
    52.1 1541.97    54.6 1540.75    65.8 1533.41    68.8 1532.31    75.5 1534.05
    95.5    1535   112.2 1533.31   132.2 1533.92   155.6 1532.89     196 1529.72
   202.7 1528.65   212.9 1528.12   226.4  1526.1  241.961524.816   256.9 1523.55
   266.9 1523.22   273.9 1523.67  278.721524.814   287.4 1528.12   294.2  1532.7
   317.7 1550.68   327.6 1555.74   330.9 1556.82   338.4 1558.33   392.2 1564.66
#Mann= 6 ,-1 , 0
       0     .04       0      70      .1       0     100     .04       0
  241.96    .045       0  278.72     .04       0  304.01      .1       0
Bank Sta=241.96,278.72
XS Rating Curve= 0 ,0
Exp/Cntr(USF)=0,0
Exp/Cntr=0.3,0.1

Type RM Length L Ch R = 1 ,7050    ,117.5,116.2,115.8
XS GIS Cut Line= 4
1993063.32736743216538.4928724591993231.97732368216562.246387423
1993375.68608922216593.1259568771993430.31917364216603.815038612
#Sta/Elev= 30
       0 1568.31     7.8 1568.24    11.2 1567.01    34.3 1551.74    47.6 1545.49
    60.9 1543.72    70.8 1536.63    74.1 1535.17   103.9 1535.22   120.5  1529.8
   133.7 1529.89     147 1532.14   193.7 1528.83   213.8 1528.81   223.9 1526.29
   233.9 1525.29     244 1522.63   250.7 1522.21   260.7 1524.58   267.5 1525.27
   270.9 1524.93   277.6 1522.26   293.9 1520.88  302.911522.353   307.8 1524.13
   320.6 1537.41   327.9  1543.6   331.2  1545.6   338.3 1547.62     373 1551.25
#Mann= 5 ,-1 , 0
       0      .1       0      50     .04       0   277.6    .045       0
  302.91     .04       0   347.3      .1       0
Bank Sta=277.6,302.91
XS Rating Curve= 0 ,0
Exp/Cntr(USF)=0,0
Exp/Cntr=0.3,0.1

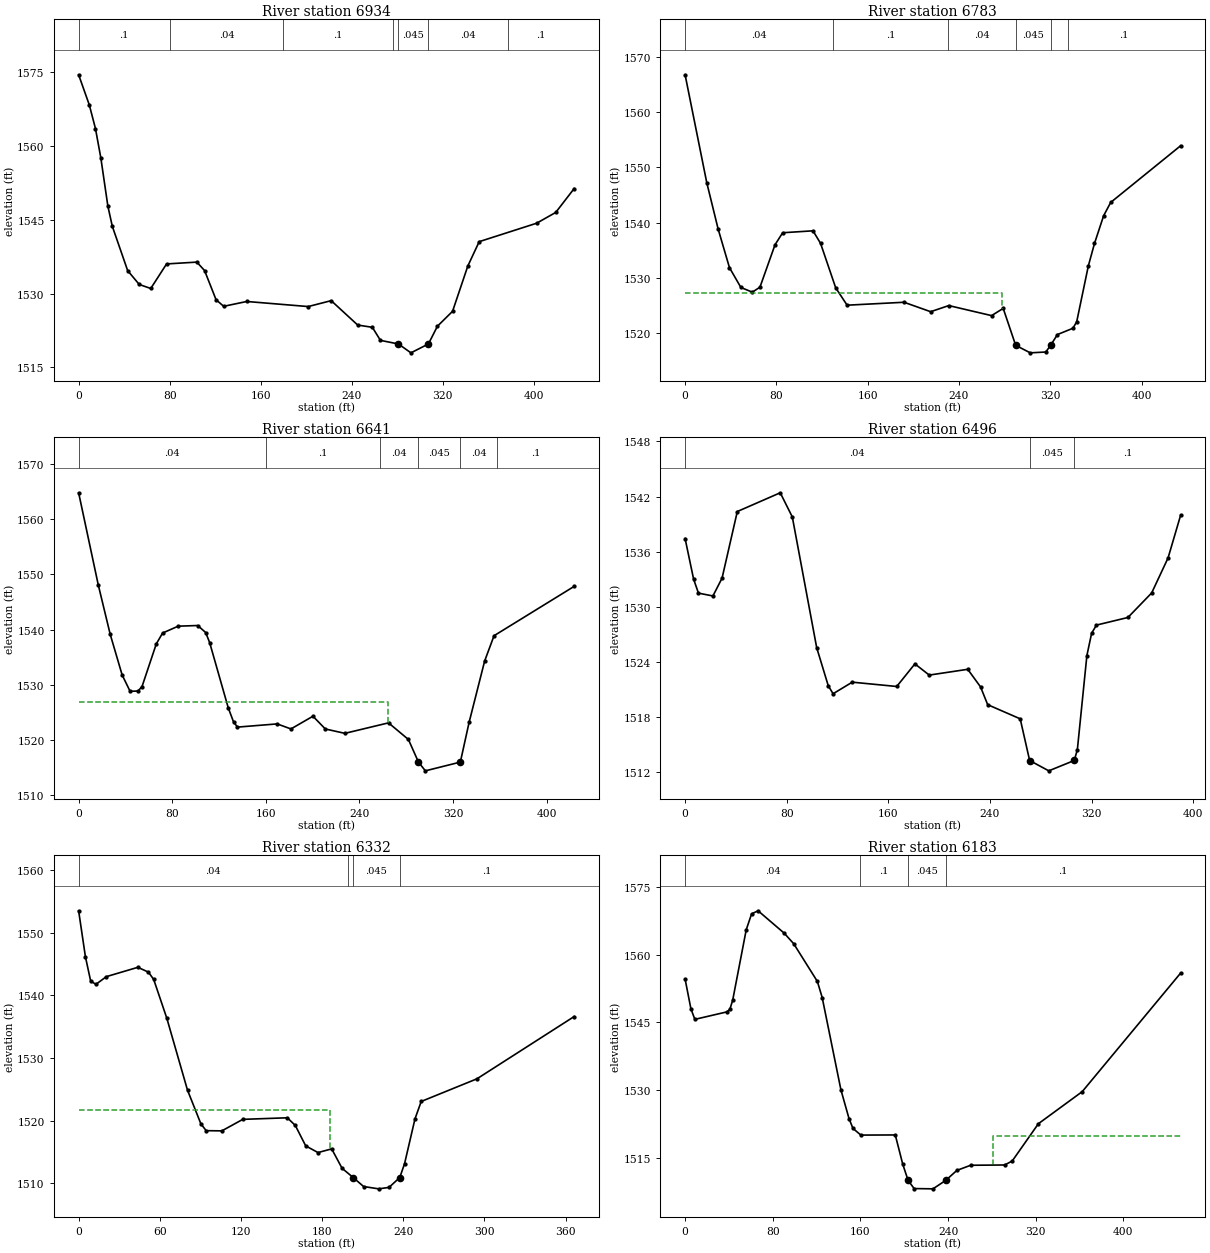
Type RM Length L Ch R = 1 ,6934    ,148.4,150.7,152
XS GIS Cut Line= 4
1993032.44779798216634.6946080661993242.66640541 216685.76466524
1993361.43398024216707.1428287081993457.63571584216728.520992176
#Sta/Elev= 30
       0 1574.39     9.4 1568.26    14.8 1563.47    19.5 1557.55    25.7 1547.74
    29.6 1543.65    43.1 1534.65    53.3 1531.84    63.4 1531.03    77.3 1536.01
   103.9 1536.38   110.7 1534.67   120.8 1528.75   127.5 1527.41   147.8 1528.39
   201.8 1527.36     222 1528.56   245.3 1523.61   258.2 1523.15   265.3  1520.5
   281.1 1519.77   292.1 1517.97  307.471519.771   315.4 1523.37   328.7  1526.4
   342.1 1535.58   352.1 1540.53   402.6 1544.27   419.4 1546.46   435.6 1551.31
#Mann= 7 ,-1 , 0
       0      .1       0      80     .04       0     180      .1       0
  276.33     .04       0   281.1    .045       0  307.47     .04       0
  377.01      .1       0
Bank Sta=281.1,307.47
XS Rating Curve= 0 ,0
Exp/Cntr(USF)=0,0
Exp/Cntr=0.3,0.1

Type RM Length L Ch R = 1 ,6783    ,141.3,141.6,142.3
XS GIS Cut Line= 4
1992980.19006505216790.2801310841993231.97732368216831.848782273
1993331.74208653216857.9776487341993406.56565867216871.042081964
#Sta/Elev= 30
       0 1566.79      19 1547.24      29 1538.82    38.9 1531.85    48.9 1528.27
    58.9 1527.42    65.6 1528.32    78.8    1536    85.5 1538.18   112.1 1538.53
   118.7 1536.27     132  1528.2     142 1525.06   191.9 1525.59   215.2 1523.88
   231.1 1524.99   268.6 1523.17   278.8 1524.48  289.721517.792   302.5 1516.43
   316.1 1516.58  320.361517.789   326.3 1519.74   339.9 1520.88   343.2 1522.05
   353.4 1532.17   358.8 1536.24   366.8 1541.26     373 1543.67   434.3 1553.94
#Mann= 6 ,-1 , 0
       0     .04       0     130      .1       0     230     .04       0
  289.72    .045       0  320.36     .04       0   335.2      .1       0
#XS Ineff= 2 , 0
          277.94 1527.29
Permanent Ineff=
       F       F
Bank Sta=289.72,320.36
XS Rating Curve= 0 ,0
Exp/Cntr(USF)=0,0
Exp/Cntr=0.3,0.1

Type RM Length L Ch R = 1 ,6641    ,139,145.8,152.1
XS GIS Cut Line= 4
1992956.43655009216903.1093271671993176.15656351216962.493114579
1993302.05019283216996.9357112771993366.18468323217010.000144508
#Sta/Elev= 30
       0 1564.78    16.8 1548.08      27 1539.14    37.2 1531.78      44 1528.82
    50.8 1528.88    54.2 1529.69    66.4 1537.42    71.8 1539.38    85.1 1540.62
   101.8 1540.74   108.6 1539.47     112 1537.65   127.9 1525.83   132.4 1523.29
   135.8 1522.34   169.7 1522.92   181.5 1522.01   200.3 1524.31   210.9    1522
   227.6 1521.21   264.9 1523.11   281.9  1520.1  290.491516.006   296.4 1514.42
   326.31516.006   333.8 1523.22   347.1 1534.33   355.1 1538.89   423.6 1547.83
#Mann= 6 ,-1 , 0
       0     .04       0     160      .1       0   257.6     .04       0
  290.49    .045       0   326.3     .04       0   357.6      .1       0
#XS Ineff= 2 , 0
          264.33 1526.82
Permanent Ineff=
       F       F
Bank Sta=290.49,326.3
XS Rating Curve= 0 ,0
Exp/Cntr(USF)=0,0
Exp/Cntr=0.3,0.1

Type RM Length L Ch R = 1 ,6496    ,161.2,163.2,163.7
XS GIS Cut Line= 4
1992963.56260458216980.3082508021993159.52910304217093.137446884
 1993249.7924599 217143.019828311993306.80089582217164.397991779
#Sta/Elev= 30
       0 1537.43     6.7 1533.01    10.5 1531.49    21.9 1531.18    29.1 1533.12
    41.1 1540.37    74.9 1542.41    84.4 1539.78   103.6 1525.55   112.7 1521.41
   116.5 1520.54   131.6  1521.8   166.6 1521.33   180.9 1523.79   192.2 1522.57
   222.5  1523.2   232.6 1521.28   238.2 1519.35   263.8 1517.81  271.231513.275
   286.3 1512.15  306.361513.278   308.8 1514.46   316.3  1524.7     320 1527.11
   323.8 1528.01   348.6 1528.84   367.3 1531.51   380.2 1535.32   390.1 1539.97
#Mann= 3 ,-1 , 0
       0     .04       0  271.23    .045       0  306.36      .1       0
Bank Sta=271.23,306.36
XS Rating Curve= 0 ,0
Exp/Cntr(USF)=0,0
Exp/Cntr=0.3,0.1

Type RM Length L Ch R = 1 ,6332    ,156.1,149.3,142.9
XS GIS Cut Line= 4
1992942.18444111217141.8321525621993068.07807042217221.406427694
1993182.09494225 217291.479296841993259.29386589217323.546542042
#Sta/Elev= 30
       0 1553.54       5 1546.21     8.9  1542.3    12.8 1541.78    20.5 1543.01
    43.8  1544.5    51.6 1543.73    55.5 1542.56    65.2 1536.36    80.5 1524.86
    90.4 1519.47    94.3 1518.38   105.9 1518.35   121.4 1520.19   154.3 1520.44
   160.2 1519.22   167.9 1515.95     177 1514.88   187.1 1515.47   194.8 1512.36
  203.01 1510.89   210.7 1509.45   221.8 1509.08   229.5 1509.31  237.45 1510.89
     241 1513.11   248.7 1520.27   253.3 1523.05   294.5 1526.67   366.4 1536.63
#Mann= 4 ,-1 , 0
       0     .04       0  198.93      .1       0  203.01    .045       0
  237.45      .1       0
#XS Ineff= 2 , 0
          185.67 1521.65
Permanent Ineff=
       F       F
Bank Sta=203.01,237.45
XS Rating Curve= 0 ,0
Exp/Cntr(USF)=0,0
Exp/Cntr=0.3,0.1

Type RM Length L Ch R = 1 ,6183    ,158.6,161,163
XS GIS Cut Line= 4
1992866.17319322217309.2944330631993019.38336475217379.367302209
1993157.15375154217423.3113048941993292.54878684217455.378550096
#Sta/Elev= 30
       0 1554.61     5.3 1548.02     8.9 1545.68    38.4 1547.35    40.9 1547.95
    43.4 1549.89    55.8 1565.53    60.7 1569.04    66.6 1569.72    90.4 1564.77
    99.1 1562.43   120.7 1554.08   125.1 1550.52   142.2 1530.07   149.6  1523.7
   153.2 1521.53   160.4 1520.06   191.8 1520.09   198.6 1513.63  203.481510.044
     209 1508.22   226.2 1508.16  237.911510.043     248 1512.24   260.6 1513.38
   291.6 1513.44   298.5 1514.32   322.4 1522.58   362.4 1529.68   452.2 1555.93
#Mann= 4 ,-1 , 0
       0     .04       0     160      .1       0  203.48    .045       0
  237.91      .1       0
#XS Ineff= 2 , 0
                           280.8         1519.76
Permanent Ineff=
       F       F
Bank Sta=203.48,237.91
XS Rating Curve= 0 ,0
Exp/Cntr(USF)=0,0
Exp/Cntr=0.3,0.1

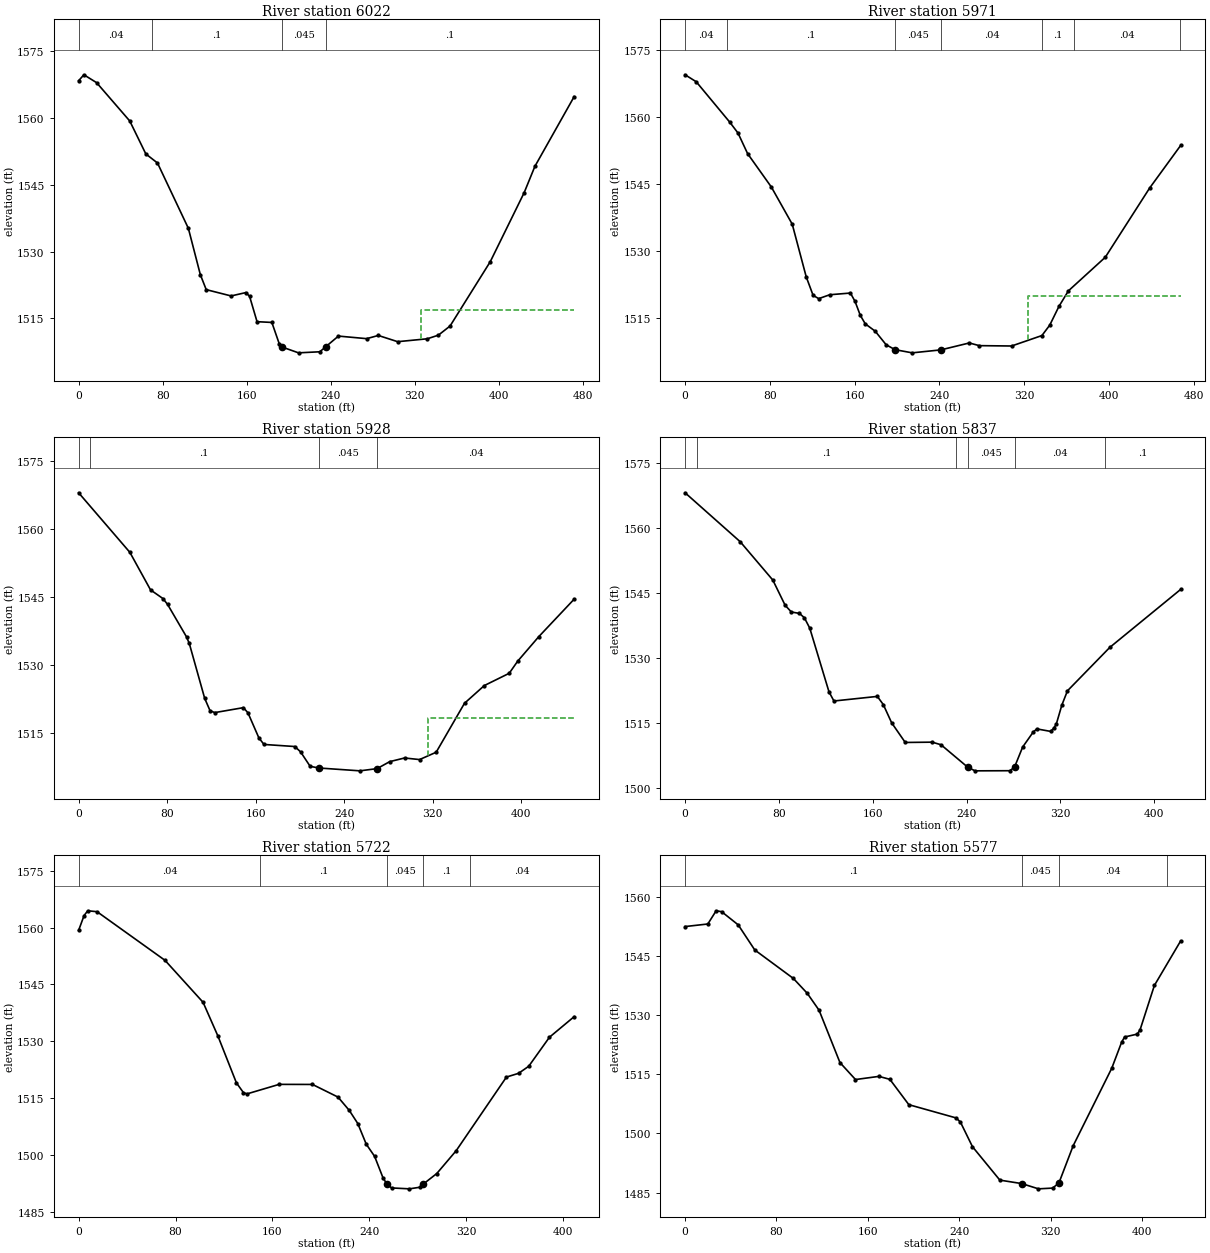
Type RM Length L Ch R = 1 ,6022    ,40.6,50.9,60.1
XS GIS Cut Line= 4
1992834.10594802217457.7539015931992955.24887434217521.888391997
1993170.21818477217606.2133701221993266.41992038217645.406669814
#Sta/Elev= 30
       0 1568.43       5 1569.76    17.1 1567.99    48.7 1559.36      64 1551.95
    75.1 1549.91   104.5 1535.21   115.9 1524.79   121.5 1521.42   145.2    1520
   159.3 1520.76   162.8 1519.91   169.9 1514.21     184 1514.04     191 1509.27
  193.331508.539   209.4  1507.2   229.7 1507.44  235.16 1508.54   247.4 1510.97
   274.3 1510.39   285.4 1511.11   303.8 1509.71     332 1510.36   342.6 1511.18
   353.7 1513.23     392 1527.71   424.3 1543.25   434.5 1549.16   471.9 1564.85
#Mann= 4 ,-1 , 0
       0     .04       0      70      .1       0  193.33    .045       0
  235.16      .1       0
#XS Ineff= 2 , 0
                          325.93         1516.88
Permanent Ineff=
       F       F
Bank Sta=193.33,235.16
XS Rating Curve= 0 ,0
Exp/Cntr(USF)=0,0
Exp/Cntr=0.3,0.1

Type RM Length L Ch R = 1 ,5971    ,39.9,43.7,45.3
XS GIS Cut Line= 4
1992832.69460975217469.3621297591992955.81359098217551.181705893
1993089.84184902217654.0406016041993203.61002155217753.003327023
#Sta/Elev= 30
       0 1569.35    10.5 1567.79      42 1558.79    49.9 1556.32      59  1551.7
    81.4 1544.23   101.1 1535.92   114.3 1524.13   120.8 1519.99   126.1 1519.26
   136.5 1520.13     156 1520.51   160.4 1518.62   165.3 1515.53     170 1513.62
   179.4 1511.97   189.7 1508.94   198.1 1507.84   214.3 1507.13   241.3 1507.79
   268.2 1509.34   277.6 1508.74   308.1 1508.66   336.7    1511   344.1 1513.33
   352.8 1517.54   361.7    1521   396.5 1528.52   438.3 1543.99   467.6 1553.53
#Mann= 7 ,-1 , 0
       0     .04       0      40      .1       0   198.1    .045       0
   241.3     .04       0  336.77      .1       0  366.77     .04       0
  466.77      .1       0
#XS Ineff= 2 , 0
                          323.31         1519.84
Permanent Ineff=
       F       F
Bank Sta=198.1,241.3
XS Rating Curve= 0 ,0
Exp/Cntr(USF)=0,0
Exp/Cntr=0.3,0.1

Type RM Length L Ch R = 1 ,5928    ,86,90.2,95.2
XS GIS Cut Line= 4
1992828.79843945217486.505279044 1992972.1775062217605.728089982
1993046.98397581217675.0799211811993163.08985052 217784.17268936
#Sta/Elev= 30
       0 1567.99    46.3 1554.83      65 1546.53    76.2 1544.62    80.4 1543.32
    97.5 1536.15     100  1534.7   113.9 1522.58   118.8 1519.82   123.1 1519.43
   148.9 1520.52     153 1519.38   162.9 1513.83   167.5 1512.39   195.4 1511.93
   200.6 1510.74   209.2 1507.56   216.91507.191   254.2 1506.56   269.7 1507.05
   281.1 1508.59   294.5  1509.4   308.1 1509.05   323.1 1510.67   348.7 1521.49
   366.6  1525.4   389.1 1528.11   396.7 1530.77   415.8  1536.2   447.8 1544.49
#Mann= 4 ,-1 , 0
       0     .04       0      10      .1       0   216.9    .045       0
   269.7     .04       0
#XS Ineff= 2 , 0
          209.02 1507.37   315.4         1518.19
Permanent Ineff=
       F       F
Bank Sta=216.9,269.7
XS Rating Curve= 0 ,0
Exp/Cntr(USF)=0,0
Exp/Cntr=0.3,0.1

Type RM Length L Ch R = 1 ,5837    ,117,115.3,113.7
XS GIS Cut Line= 4
1992804.41405432217512.3869860111992930.30768363217669.160184779
1992993.25449829  217755.86051441993071.64109767217838.997816776
#Sta/Elev= 30
       0 1568.06      47 1556.76    74.8 1547.91    85.3 1542.09    90.6 1540.54
    97.5 1540.22   101.7 1539.21   106.3 1536.81   122.7  1522.1   126.9    1520
   163.9 1521.06     169 1519.17   176.1 1514.97   187.7 1510.43   210.7  1510.5
   218.2  1509.9  240.871504.742   247.2 1503.88   276.9 1503.91  280.87 1504.74
   287.8 1509.37   296.8 1512.83   299.9 1513.56   311.7 1512.98   314.4 1513.73
   316.5 1514.68   321.2 1519.04     326 1522.35   362.1 1532.37   422.5 1545.75
#Mann= 6 ,-1 , 0
       0     .04       0      10      .1       0  231.06     .04       0
  240.87    .045       0  280.87     .04       0  358.21      .1       0
Bank Sta=240.87,280.87
XS Rating Curve= 0 ,0
Exp/Cntr(USF)=0,0
Exp/Cntr=0.3,0.1

Type RM Length L Ch R = 1 ,5722    ,140.2,145.2,146.5
XS GIS Cut Line= 4
1992722.46442769217568.2077461791992836.48129952217741.608405421
1992904.17881717217822.3703563011992965.93795608217896.006252691
#Sta/Elev= 30
       0 1559.27     4.5 1563.17     7.5 1564.43    15.2 1564.19    71.3 1551.35
   102.7 1540.28     115 1531.35   130.2 1519.04     136 1516.45   138.9  1516.1
   165.5 1518.62     193  1518.6   214.1 1515.26   223.4 1511.74   230.4 1508.29
   237.4 1502.83   244.3 1499.62   251.3 1493.89  254.621492.244   258.3 1491.29
     273 1491.05   281.6 1491.47  284.211492.247   295.6 1495.09   311.6 1501.11
   353.1 1520.55   363.1 1521.53   371.5  1523.4   388.6 1531.06     409 1536.49
#Mann= 5 ,-1 , 0
       0     .04       0     150      .1       0  254.62    .045       0
  284.21      .1       0  322.91     .04       0
Bank Sta=254.62,284.21
XS Rating Curve= 0 ,0
Exp/Cntr(USF)=0,0
Exp/Cntr=0.3,0.1

Type RM Length L Ch R = 1 ,5577    ,176.1,184.8,185
XS GIS Cut Line= 4
1992625.07501633217616.9024518561992734.34118517217815.244301812
1992797.28799983217923.3227949011992836.48129952217995.771015543
#Sta/Elev= 30
       0 1552.41    19.9 1553.06    27.2 1556.41      32 1556.18    46.5 1552.84
      61 1546.48    94.8 1539.26   106.9 1535.52   117.3 1531.21   135.6 1517.94
   149.2 1513.64   169.7 1514.44   179.3 1513.69   195.9 1507.27   237.3 1503.91
   241.1 1502.85   251.6 1496.63   275.6 1488.15   294.8 1487.27   309.4 1485.94
   321.9 1486.13  327.391487.478   339.8 1496.86   373.6 1516.51   382.2 1523.08
   384.8 1524.42     396 1525.16   398.4 1526.26   410.9 1537.48   433.9 1548.76
#Mann= 4 ,-1 , 0
       0      .1       0   294.8    .045       0  327.39     .04       0
  421.52      .1       0
Bank Sta=294.8,327.39
XS Rating Curve= 0 ,0
Exp/Cntr(USF)=0,0
Exp/Cntr=0.3,0.1

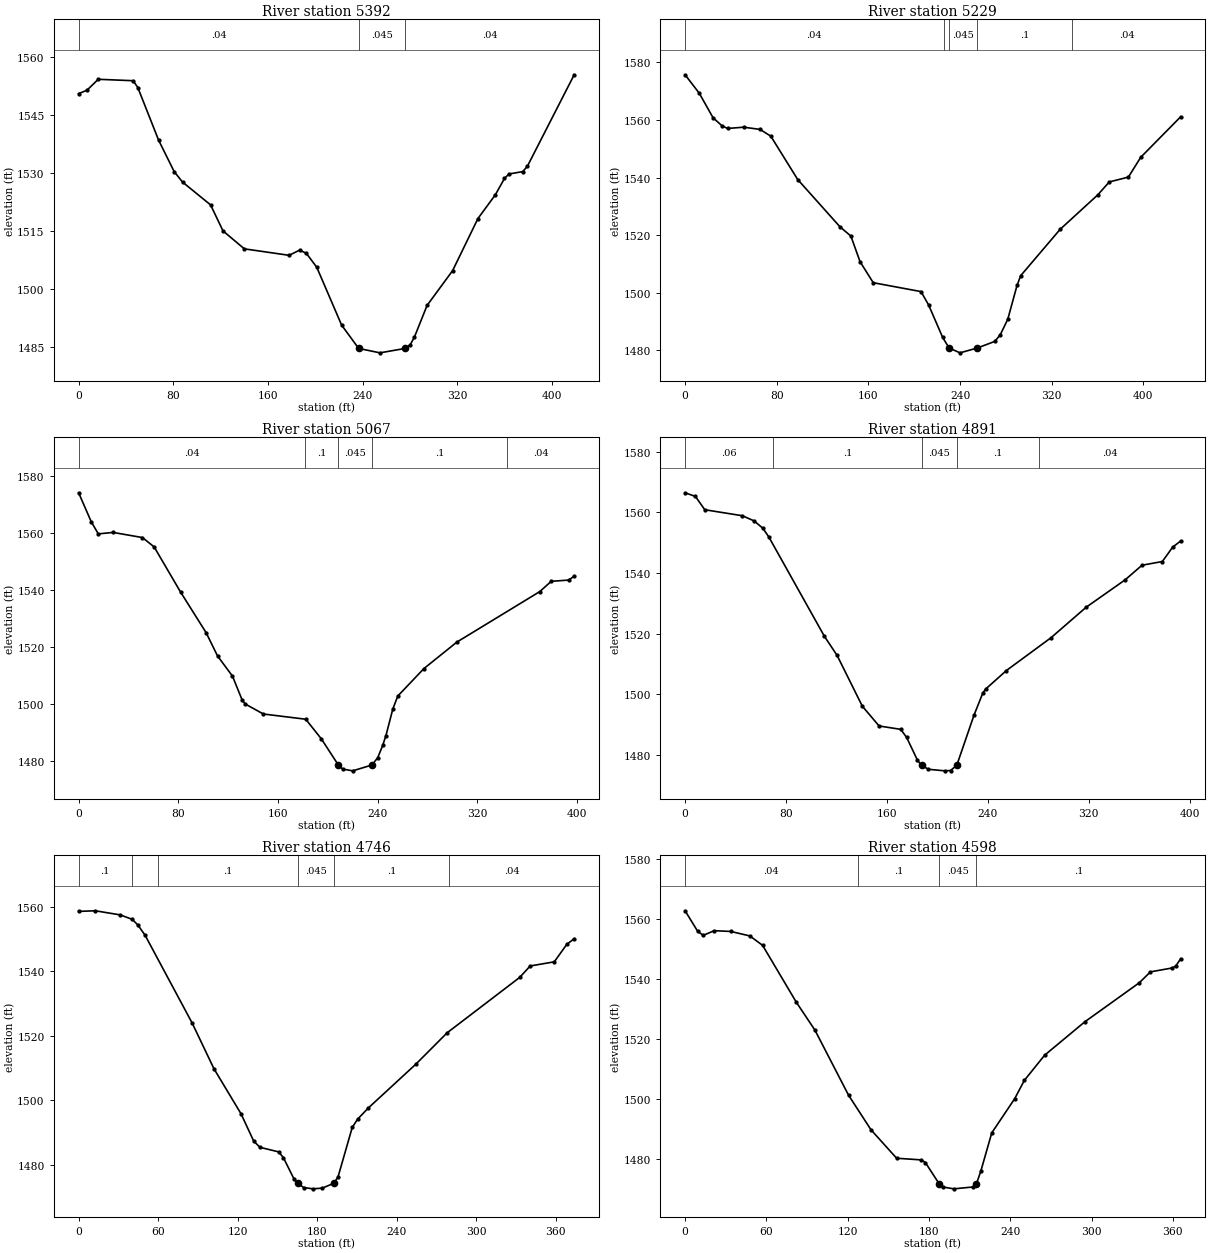
Type RM Length L Ch R = 1 ,5392    ,166.1,163.2,160.1
XS GIS Cut Line= 4
 1992476.6155478217707.1658087221992578.75566215217865.126683237
1992622.69966484217964.8914460891992686.83415524218068.219236186
#Sta/Elev= 30
       0 1550.62       7 1551.49    16.6 1554.34    46.1 1553.97      50  1552.2
    67.6 1538.53    80.7  1530.4    87.8 1527.67   111.5 1521.75     122    1515
     140 1510.35   177.9 1508.67   186.7 1510.02   192.4 1509.19   201.2 1505.58
   222.2 1490.57  236.621484.512   254.6 1483.37  275.871484.512   280.1 1485.42
   283.7 1487.44   294.4 1495.67     316  1504.7   337.4 1518.22   352.1 1524.37
   359.8 1528.61   363.6 1529.77   375.3 1530.39   379.2  1531.8   418.7 1555.51
#Mann= 3 ,-1 , 0
       0     .04       0  236.62    .045       0  275.87     .04       0
Bank Sta=236.62,275.87
XS Rating Curve= 0 ,0
Exp/Cntr(USF)=0,0
Exp/Cntr=0.3,0.1

Type RM Length L Ch R = 1 ,5229    ,164.2,161.5,160.1
XS GIS Cut Line= 4
1992330.74511769217801.3454868171992420.13797585217928.730309684
1992496.12190527218060.5847754591992569.87101325218161.151740881
#Sta/Elev= 30
       0  1575.7    12.4 1569.27    24.4 1560.77    32.3 1557.95    37.1 1557.05
    51.2 1557.49    65.4 1556.72    74.8 1554.37    98.3  1539.3   135.1 1522.91
   144.7 1519.65   152.7 1510.76   164.2 1503.46   205.9 1500.37   212.5 1495.75
   224.8 1484.45  230.36 1480.79   239.9 1479.09  255.191480.792   270.2 1483.05
     275  1485.3   281.6 1490.73   289.7  1502.5   292.9  1505.9   327.3 1521.99
   360.2 1533.98   370.2 1538.47   386.9 1540.15   397.6    1547   432.5  1561.1
#Mann= 5 ,-1 , 0
       0     .04       0  225.62      .1       0  230.36    .045       0
  255.19      .1       0   337.8     .04       0
Bank Sta=230.36,255.19
XS Rating Curve= 0 ,0
Exp/Cntr(USF)=0,0
Exp/Cntr=0.3,0.1

Type RM Length L Ch R = 1 ,5067    ,180.1,176.8,168.8
XS GIS Cut Line= 4
1992212.29958064217926.4954882311992292.75315298218042.706203829
1992375.44154677218158.9169194271992458.12994056 218237.13567031
#Sta/Elev= 30
       0 1573.99    10.1 1563.85    15.8 1559.57    27.6 1560.09    51.2 1558.29
    60.6 1555.02    81.8  1539.2   102.4 1524.89   111.5 1516.77   123.5  1509.7
   131.2 1501.39   133.7 1499.93   148.3 1496.41   182.3 1494.58   194.9 1487.66
  208.471478.529   211.9  1477.1     220 1476.48  235.461478.531   240.1 1481.09
   244.1  1485.4   246.7 1488.85   252.2 1498.13   256.2 1502.71   277.2 1512.35
   303.6 1521.62   370.2 1539.34   379.4 1542.94   393.4 1543.38   397.8 1544.75
#Mann= 5 ,-1 , 0
       0     .04       0  181.34      .1       0  208.47    .045       0
  235.46      .1       0  343.97     .04       0
Bank Sta=208.47,235.46
XS Rating Curve= 0 ,0
Exp/Cntr(USF)=0,0
Exp/Cntr=0.3,0.1

Type RM Length L Ch R = 1 ,4891    ,145.9,144.5,140.8
XS GIS Cut Line= 4
 1992073.7406505218091.8722758131992136.31565121218161.151740881
1992254.76118826218263.9535277561992370.97190386218346.641921547
#Sta/Elev= 30
       0 1566.47     8.2 1565.26    15.6 1560.87    45.4 1558.89    54.7 1557.18
    61.6 1554.77    66.3 1551.93   110.4 1519.09   120.5 1512.76   140.5 1495.98
   153.8 1489.46   170.9 1488.35   175.6 1485.69   184.2 1478.15  187.441476.454
   192.9 1475.16   205.8 1474.65   210.4 1474.76  215.331476.455     229 1493.02
     236 1500.35   238.3 1501.67   254.7 1507.78     290 1518.59   317.9 1528.67
   348.8 1537.72   362.2 1542.55   378.3 1543.77   386.5 1548.53   392.8 1550.54
#Mann= 5 ,-1 , 0
       0     .06       0      70      .1       0  187.44    .045       0
  215.33      .1       0  280.19     .04       0
Bank Sta=187.44,215.33
XS Rating Curve= 0 ,0
Exp/Cntr(USF)=0,0
Exp/Cntr=0.3,0.1

Type RM Length L Ch R = 1 ,4746    ,150.2,147.8,150.3
XS GIS Cut Line= 4
1991995.52189962218246.0749561261992087.14957923218315.354421194
1992205.59511628218398.0428149851992301.69243879218460.617815692
#Sta/Elev= 30
       0 1558.57    12.6 1558.76    31.3 1557.49    40.4 1556.12    44.6  1554.4
    50.1 1551.22    85.7 1523.95   102.1 1509.82   122.5 1495.88   132.1  1487.4
   136.8 1485.45     151 1484.02   154.5 1482.27   162.5 1475.67  165.231474.326
   169.8 1472.98   176.9 1472.57     184  1472.8  192.751474.325   195.8  1476.3
   206.5  1491.6   210.5 1494.14   218.5 1497.58   254.7 1511.29   278.1 1520.93
   332.9 1538.11   340.8 1541.65     359 1542.94   368.4 1548.34     374 1550.09
#Mann= 6 ,-1 , 0
       0      .1       0      40     .04       0      60      .1       0
  165.23    .045       0  192.75      .1       0  279.32     .04       0
Bank Sta=165.23,192.75
XS Rating Curve= 0 ,0
Exp/Cntr(USF)=0,0
Exp/Cntr=0.3,0.1

Type RM Length L Ch R = 1 ,4598    ,187.9,184.9,180.5
XS GIS Cut Line= 4
1991921.77279165218375.6946004471992008.93082834218438.269601154
 1992127.3763654218520.9579949451992227.94333082218574.593709836
#Sta/Elev= 30
       0 1562.86     9.3    1556    13.4 1554.67    21.5 1556.22    33.7 1555.97
    47.8 1554.47    57.2 1551.33      82 1532.43    95.8 1523.09   120.7 1501.32
   137.2 1489.84   156.1 1480.36   174.3 1479.81   177.3 1478.94  187.641471.736
   190.3 1470.77   198.3 1470.16   212.6 1470.79  214.941471.731   218.3 1476.15
   226.3 1488.81   243.3 1500.26   250.3 1506.28   265.3  1514.7     295 1525.85
   335.2 1538.86   343.4 1542.49   359.4 1543.79     362 1544.38   365.7 1546.84
#Mann= 4 ,-1 , 0
       0     .04       0  127.29      .1       0  187.64    .045       0
  214.94      .1       0
Bank Sta=187.64,214.94
XS Rating Curve= 0 ,0
Exp/Cntr(USF)=0,0
Exp/Cntr=0.3,0.1

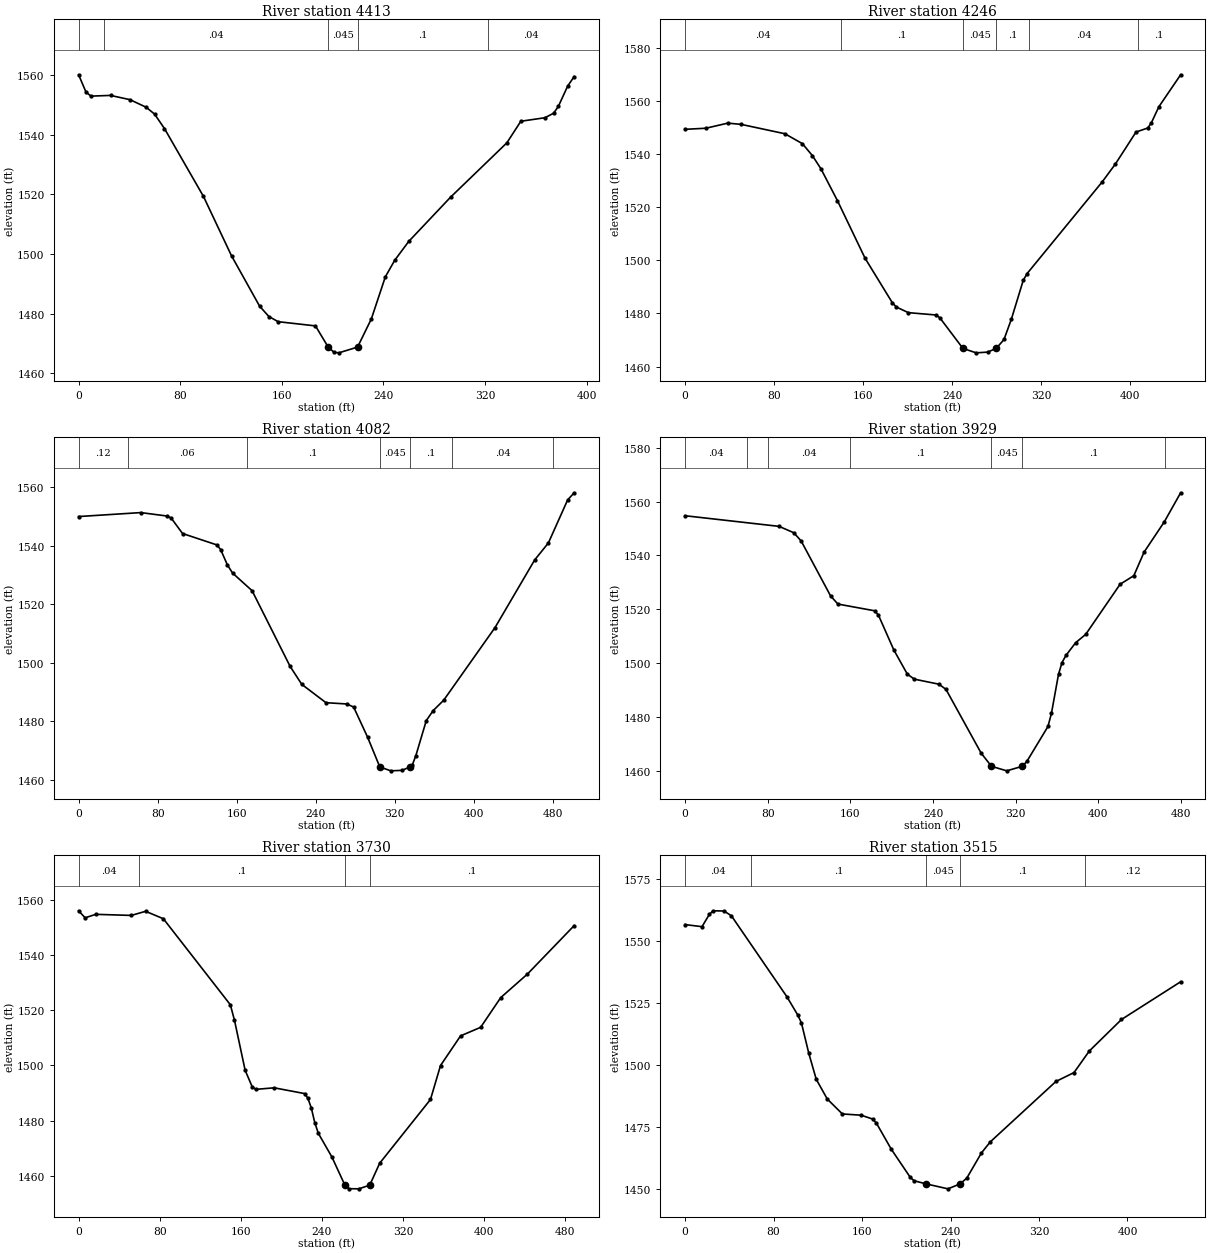
Type RM Length L Ch R = 1 ,4413    ,167,167.4,165.5
XS GIS Cut Line= 4
1991839.08439785218563.4196025671991926.24243455218617.055317459
1992087.14957923218697.5088897961992183.24690174 218746.67496178
#Sta/Elev= 30
       0 1560.15     5.8 1554.34     9.7 1552.99    25.1 1553.23    40.5 1551.79
    53.2 1549.25    59.8 1546.96    67.6  1542.1    98.3 1519.34   120.4 1499.41
   142.5 1482.53   149.8 1479.06   157.1 1477.32   186.5 1475.91  196.491468.804
   201.1 1467.05   204.9 1466.87  219.641468.803   230.5 1478.26   241.5 1492.36
   248.9 1497.92   259.9 1504.23   292.9  1519.1   337.2 1537.32   348.2 1544.56
   367.2 1545.74     374 1547.26   377.7 1549.51   385.1 1556.37   390.2 1559.55
#Mann= 5 ,-1 , 0
       0      .1       0      20     .04       0  196.49    .045       0
  219.64      .1       0  322.24     .04       0
Bank Sta=196.49,219.64
XS Rating Curve= 0 ,0
Exp/Cntr(USF)=0,0
Exp/Cntr=0.3,0.1

Type RM Length L Ch R = 1 ,4246    ,164.1,164.2,162.4
XS GIS Cut Line= 4
1991756.39600406218695.2740683421991897.18975565218789.136569402
1992051.39243597218853.9463915631992158.66386575218871.824963193
#Sta/Elev= 30
       0  1549.3    18.6  1549.7    38.3 1551.62    50.2 1551.17    89.6 1547.64
   105.4  1543.9   114.4 1539.38     122 1534.47   136.9 1522.43   161.7 1500.78
   186.3 1483.97   189.9  1482.4   200.6 1480.31   225.5 1479.43     229  1478.3
  249.62 1466.85   261.5 1465.19   271.7 1465.46  279.541466.848   286.5 1470.22
   293.1 1477.81   303.8 1492.48   307.3 1495.04   374.6 1529.45   386.6 1536.25
   405.1 1548.27   415.7  1549.8     419 1551.83   425.6 1557.77   445.2 1569.82
#Mann= 6 ,-1 , 0
       0     .04       0     140      .1       0  249.62    .045       0
  279.54      .1       0  309.21     .04       0  406.48      .1       0
Bank Sta=249.62,279.54
XS Rating Curve= 0 ,0
Exp/Cntr(USF)=0,0
Exp/Cntr=0.3,0.1

Type RM Length L Ch R = 1 ,4082    ,156.7,152.4,151.9
XS GIS Cut Line= 4
1991685.62665803218841.2824033241991854.47983454218945.574071169
1992053.13063043219020.0681196291992142.52348858 219037.45006427
#Sta/Elev= 30
       0 1550.02      63 1551.37    89.8 1550.18    93.7  1549.5   105.2 1544.22
   139.9 1540.33   143.8 1538.72   150.6 1533.49   155.9 1530.69   175.6 1524.68
   214.1 1498.82   225.9 1492.68   250.4 1486.41   271.4 1485.97   278.4 1484.93
   292.5 1474.66  304.931464.441   316.1 1463.12   327.5 1463.29  335.271464.443
     338 1465.28   341.4  1468.3     352 1480.32     359 1483.72   369.6 1487.25
   421.6 1512.09   461.7 1535.18   475.6    1541   495.1 1555.71   501.7 1558.14
#Mann= 7 ,-1 , 0
       0     .12       0      50     .06       0     170      .1       0
  304.93    .045       0  335.27      .1       0  378.46     .04       0
  480.62      .1       0
Bank Sta=304.93,335.27
XS Rating Curve= 0 ,0
Exp/Cntr(USF)=0,0
Exp/Cntr=0.3,0.1

Type RM Length L Ch R = 1 ,3929    ,199.4,199.6,197.5
XS GIS Cut Line= 4
1991678.17725318219034.9669293211991866.89550928219114.427247679
 1992020.8498761219156.6405418071992135.07408374219171.539351499
#Sta/Elev= 30
       0 1554.77      91 1550.82   105.2 1548.45   112.3 1545.41   140.8 1524.99
   147.9 1521.95   183.5 1519.45   187.1 1517.86     202 1504.91   215.1 1495.91
   221.9 1494.05   245.7 1492.18   252.5 1490.25   286.5 1466.59  296.511461.673
   311.3 1459.99  326.281461.672   330.8 1463.51   351.2 1476.47   354.6 1481.43
   361.4 1495.86   364.8 1500.24   368.6 1502.87     378 1507.61   387.7 1510.68
     421 1529.31   434.3  1532.5   444.2 1541.24   463.8 1552.51   479.6  1563.3
#Mann= 7 ,-1 , 0
       0     .04       0      60      .1       0      80     .04       0
     160      .1       0  296.51    .045       0  326.28      .1       0
   464.4     .04       0
Bank Sta=296.51,326.28
XS Rating Curve= 0 ,0
Exp/Cntr(USF)=0,0
Exp/Cntr=0.3,0.1

Type RM Length L Ch R = 1 ,3730    ,213.2,214.3,215.9
XS GIS Cut Line= 4
1991670.72784833219248.5165349081991854.47983454219318.044313471
1991978.63658197219347.8419328551992142.52348858219365.223877496
#Sta/Elev= 30
       0 1556.03     6.4 1553.48    16.9 1554.74      52 1554.35    66.1 1555.84
    83.6 1553.15   149.7 1521.99   153.8 1516.36   164.3 1498.25   171.3 1492.24
   174.8 1491.33     193 1491.89   222.9 1489.81   226.2 1488.13   229.6  1484.6
     233 1479.32   236.5 1475.43   249.9 1466.84  262.741456.628   266.7 1455.34
   276.5 1455.29  287.261456.633   297.1 1464.58   347.2 1487.66   357.1 1499.96
   376.9 1510.71   396.7  1513.8   416.5 1524.56   442.9 1533.11     489 1550.66
#Mann= 4 ,-1 , 0
       0     .04       0      60      .1       0  262.74    .045       0
  287.26      .1       0
Bank Sta=262.74,287.26
XS Rating Curve= 0 ,0
Exp/Cntr(USF)=0,0
Exp/Cntr=0.3,0.1

Type RM Length L Ch R = 1 ,3515    ,190,180.7,169.4
XS GIS Cut Line= 4
1991668.24471338219496.8300297761991794.88459577219519.178244314
1991961.25463733219566.357808339 1992107.7595993219561.391538442
#Sta/Elev= 30
       0 1556.48    15.3 1555.64    21.9 1560.56    25.3 1562.04    35.3 1561.94
    41.9    1560    91.9 1527.54   101.9 1520.08   105.2 1516.91   111.9 1504.61
   118.6 1494.21   128.6 1486.26   142.2 1480.28   159.2 1479.77   169.5 1478.24
   172.9 1476.66   186.5 1466.04   203.6 1454.78     207 1453.41  217.64 1452.17
   237.7 1450.14  248.86 1452.17   254.8 1454.51     268 1464.61     276 1469.05
   335.3 1493.34   351.7 1496.94   365.5  1505.6   394.6 1518.29   448.1 1533.47
#Mann= 5 ,-1 , 0
       0     .04       0      60      .1       0  217.64    .045       0
  248.86      .1       0  361.53     .12       0
Bank Sta=217.64,248.86
XS Rating Curve= 0 ,0
Exp/Cntr(USF)=0,0
Exp/Cntr=0.3,0.1