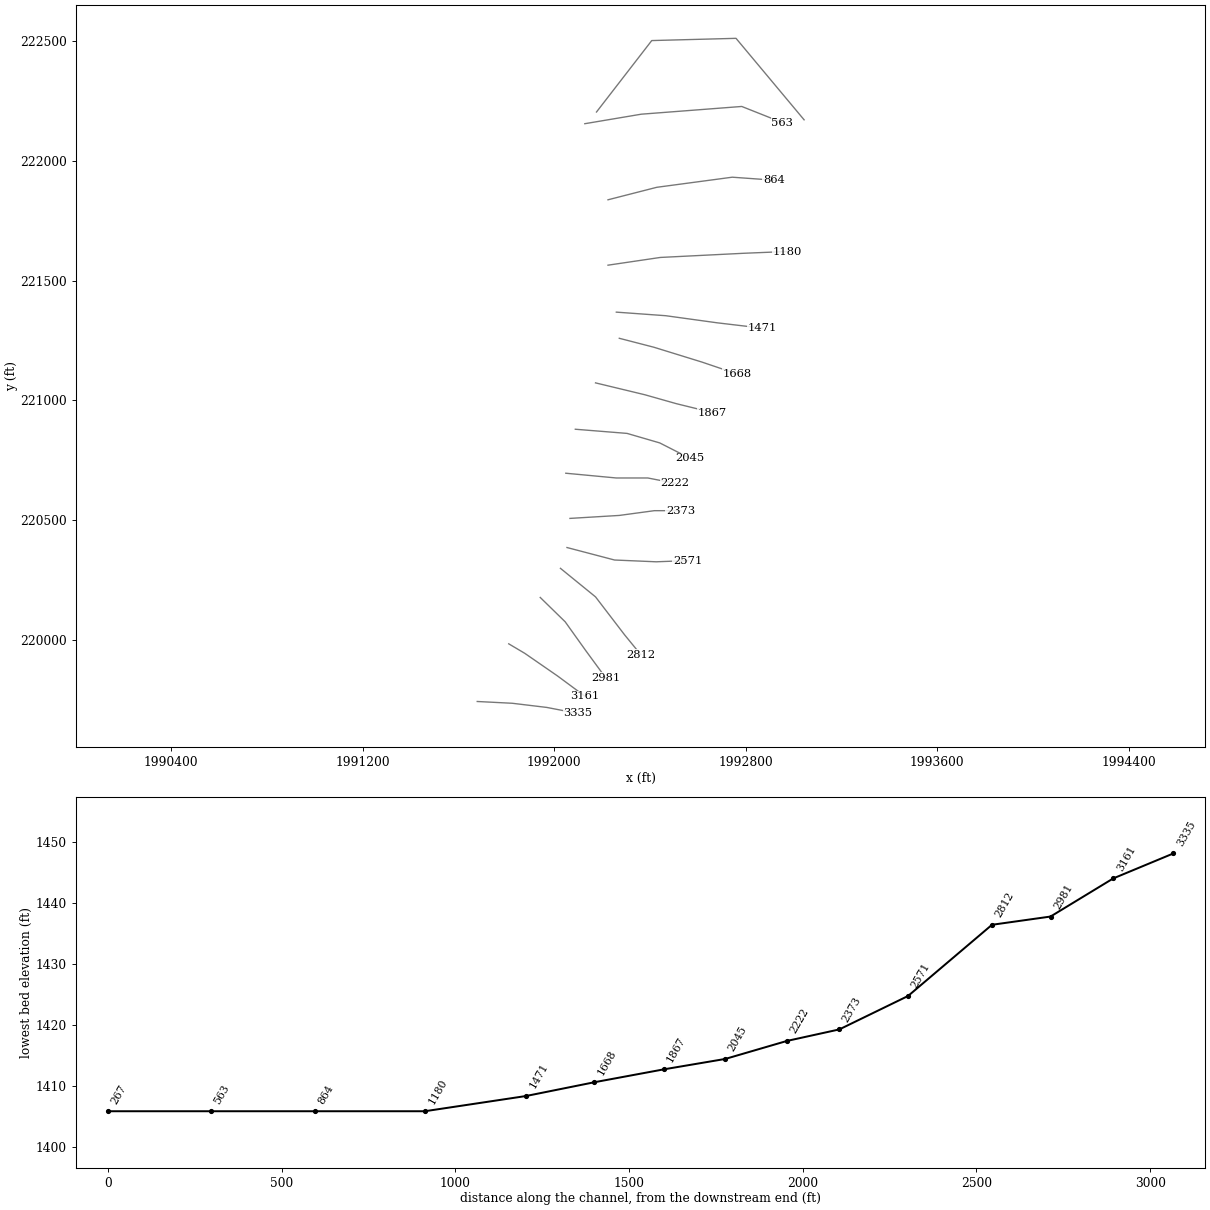
HEC-RAS study PIPESTCK1_A.prj: PIPESTCK1_A

--- PIPESTCK1_A.g01 (geometry) --- (continued)

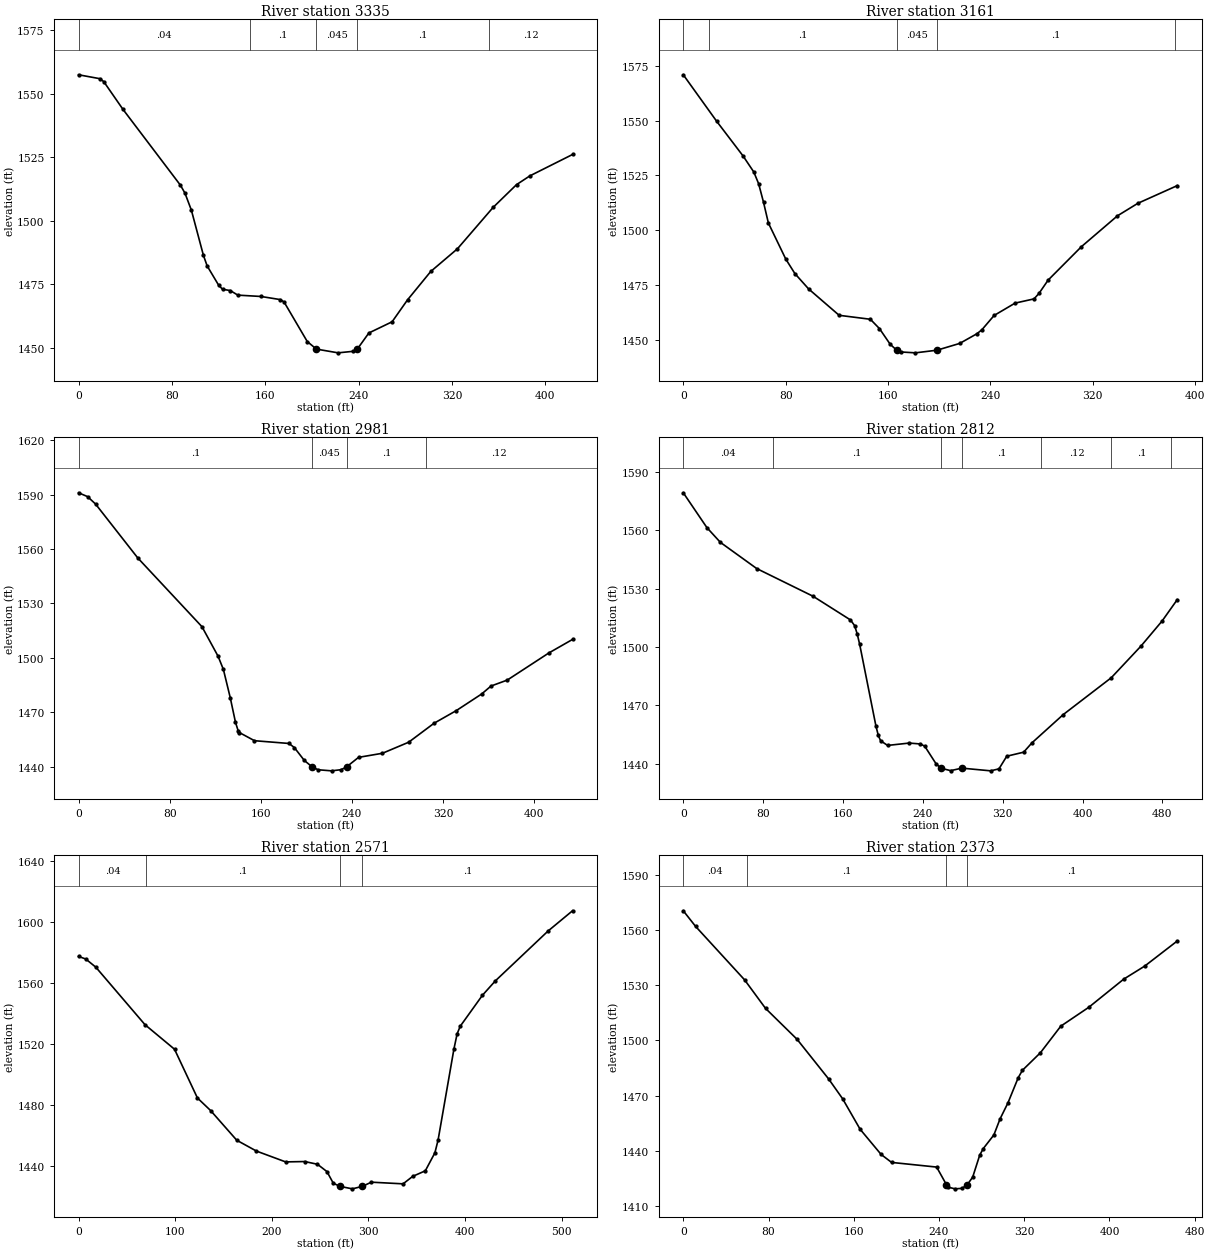
Type RM Length L Ch R = 1 ,3335    ,185.7,173.3,160
XS GIS Cut Line= 4
1991678.17725318219742.6603896951991824.68221515219735.210984849
1991968.70404218219717.8290402081992097.82705951219692.997690722
#Sta/Elev= 30
       0 1557.49    18.3 1555.95    21.6 1554.79      38 1543.92    87.3 1514.04
    91.2  1510.9    96.7 1504.19     107 1486.45   110.2 1482.27   120.1 1474.65
   123.4 1473.09     130 1472.58   136.5 1470.78   156.3 1470.25   172.8 1469.03
   176.1 1468.09     196 1452.51  203.84 1449.54   222.4 1448.07   235.6 1448.68
  238.861449.539   248.8 1455.89   268.7 1460.29   281.9 1468.91   301.8 1480.08
   324.7 1489.02   355.3 1505.32   375.3 1514.25   386.7 1517.69   423.3 1526.12
#Mann= 5 ,-1 , 0
       0     .04       0  146.69      .1       0  203.84    .045       0
  238.86      .1       0  351.76     .12       0
Bank Sta=203.84,238.86
XS Rating Curve= 0 ,0
Exp/Cntr(USF)=0,0
Exp/Cntr=0.3,0.1

Type RM Length L Ch R = 1 ,3161    ,190.4,180.5,172.9
XS GIS Cut Line= 4
1991809.78340546219983.5244797171991876.82804907219943.794320538
1992013.40047125219849.4351924891992127.62467889219765.008604233
#Sta/Elev= 30
       0 1570.95      26 1549.79    46.7 1533.89    55.1 1526.56    58.9 1521.18
    62.7 1512.73    66.5 1503.26    80.1 1486.78    87.2 1480.18    97.9 1473.18
   121.8 1461.11   146.2  1459.3   153.3 1455.04   161.7 1447.88  166.791445.177
   169.9 1444.37   181.4 1443.97  198.271445.177     216 1448.27   229.5  1452.7
   233.4 1454.54   242.9 1461.04   259.3 1466.68   274.1 1468.61     278 1471.14
   285.1 1477.18   311.1 1492.44   339.3 1506.55   355.2 1512.25     386 1520.33
#Mann= 5 ,-1 , 0
       0     .06       0      20      .1       0  166.79    .045       0
  198.27      .1       0  383.93     .12       0
Bank Sta=166.79,198.27
XS Rating Curve= 0 ,0
Exp/Cntr(USF)=0,0
Exp/Cntr=0.3,0.1

Type RM Length L Ch R = 1 ,2981    ,167.8,168.5,168.9
XS GIS Cut Line= 4
1991941.38955774220177.2090057141992045.68122558220075.400472818
1992132.59094879219953.7268603331992214.53440209219841.985787642
#Sta/Elev= 30
       0    1591     7.9 1588.89    14.9 1584.82      52 1555.08   108.4 1517.16
   122.5 1500.93   127.2 1493.61   133.2 1478.11   137.8 1464.52   140.1 1459.93
   141.2 1458.84   154.5 1454.33   184.8 1452.81   189.5 1450.56   198.3 1443.43
  205.111439.907   210.4 1438.31   222.2 1437.72   230.6 1438.36  235.391439.908
   245.9 1445.15   266.9 1447.41   289.9 1453.49   312.2 1463.95   331.7 1470.91
     354 1480.08   362.2 1484.46   376.5 1487.75   413.1 1502.73   433.8 1510.15
#Mann= 4 ,-1 , 0
       0      .1       0  205.11    .045       0  235.39      .1       0
  305.27     .12       0
Bank Sta=205.11,235.39
XS Rating Curve= 0 ,0
Exp/Cntr(USF)=0,0
Exp/Cntr=0.3,0.1

Type RM Length L Ch R = 1 ,2812    ,224.8,241.6,261.1
XS GIS Cut Line= 4
1992025.81614599  220298.88261821992172.32110797220179.692140663
1992293.99472045220020.7715039471992361.03936407219938.828050641
#Sta/Elev= 30
       0 1579.38    23.7 1561.44    37.2 1553.87    73.6  1540.4     130 1526.17
   167.5 1513.98   171.7 1511.04   174.3 1506.68   176.7  1501.5     193 1459.47
   195.4 1454.56   197.7 1451.84   204.7 1449.44   226.3 1450.65   237.5  1450.2
   241.9 1449.05   253.3 1439.96  258.431437.681   267.9 1436.47   279.1 1437.76
     308 1436.37   316.3  1437.4   324.1 1443.89     341 1445.96   349.3 1450.75
   380.7 1465.31   428.8 1484.25   458.5 1500.49   479.7 1513.41   494.9 1524.41
#Mann= 7 ,-1 , 0
       0     .04       0      90      .1       0  258.43    .045       0
   279.1      .1       0  358.87     .12       0  429.02      .1       0
  489.02     .12       0
Bank Sta=258.43,279.1
XS Rating Curve= 0 ,0
Exp/Cntr(USF)=0,0
Exp/Cntr=0.3,0.1

Type RM Length L Ch R = 1 ,2571    ,194.2,197.8,201.1
XS GIS Cut Line= 4
1992053.13063043220385.7923414031992251.78142632220333.646507481
1992425.60087273220326.1971026351992557.20702501220331.163372532
#Sta/Elev= 30
       0 1577.28     7.5 1575.55    17.9 1570.18    68.8 1532.42    99.3 1516.34
     123 1484.34   136.6 1476.12   163.7  1456.6   184.1 1449.48   214.3 1442.38
     234 1442.62   247.2 1440.83     257 1436.03   263.6 1428.37  270.521426.307
   283.3  1424.7  293.521426.306     303 1429.07   335.8 1427.98   345.7 1432.87
   358.8 1436.54   368.7 1448.34     372 1456.69   388.4  1516.5   391.7 1526.43
   394.9 1531.42   417.9 1551.77   431.3 1561.24   485.9    1594   511.1 1607.23
#Mann= 4 ,-1 , 0
       0     .04       0      70      .1       0  270.52    .045       0
  293.52      .1       0
Bank Sta=270.52,293.52
XS Rating Curve= 0 ,0
Exp/Cntr(USF)=0,0
Exp/Cntr=0.3,0.1

Type RM Length L Ch R = 1 ,2373    ,153.4,150.9,148.5
XS GIS Cut Line= 4
1992065.54630517220507.4659538891992271.64650591220519.881628632
1992418.15146789220539.7467082221992527.40940563220539.746708222
#Sta/Elev= 30
       0 1570.64    11.5 1562.17    57.5 1533.05    77.2 1517.49   106.8 1500.65
   136.4 1479.08   149.5 1468.31     166 1451.65   185.7 1437.93   195.5 1433.61
   237.8 1431.07     2471421.465   248.4 1420.17     255 1419.22   261.7 1419.49
  266.491421.466   271.6 1425.56   278.2 1437.53   281.5 1441.11   291.5 1448.56
   297.3  1457.3   304.7    1466   314.4  1479.8   318.3 1483.78   335.2 1493.34
   354.3  1507.8   380.6 1518.09   413.4 1533.43   433.1 1540.53   463.6 1554.18
#Mann= 4 ,-1 , 0
       0     .04       0      60      .1       0     247    .045       0
  266.49      .1       0
Bank Sta=247,266.49
XS Rating Curve= 0 ,0
Exp/Cntr(USF)=0,0
Exp/Cntr=0.3,0.1

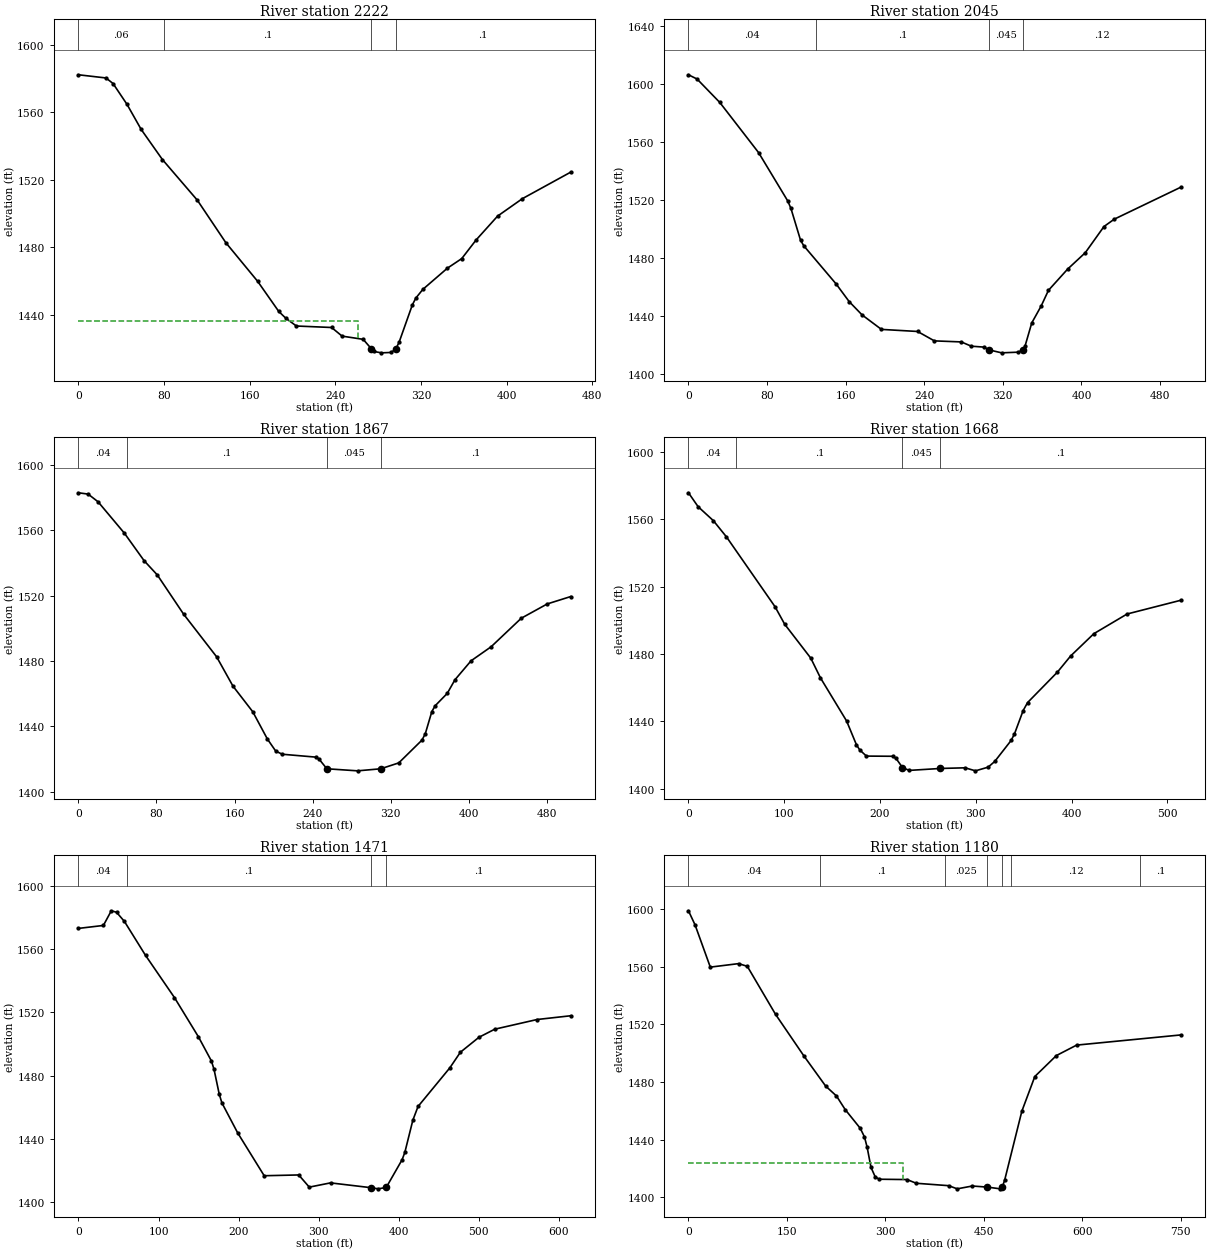
Type RM Length L Ch R = 1 ,2222    ,179.4,177.5,169.5
XS GIS Cut Line= 4
1992048.16436053220696.1842099881992259.23083117220676.319130399
1992390.83698345220676.3191303991992505.06119109220653.970915861
#Sta/Elev= 30
       0 1582.12    25.7 1580.23    32.3 1576.94    45.3 1564.64    58.6 1549.72
    78.4  1531.9   111.1 1507.76   137.7  1482.6   167.4 1459.72   187.1 1441.89
   193.7 1437.85   203.6 1433.23   236.5 1432.35   246.3 1427.24     266 1425.33
  273.761419.671   275.8 1418.15   283.1 1417.33   292.2 1417.56  296.461419.674
   299.5 1423.49   311.9 1445.68   315.2 1449.78   321.8 1454.97   344.7 1467.51
   358.1 1473.19   371.5 1484.21   391.6 1498.37   414.8 1508.72     460 1524.45
#Mann= 4 ,-1 , 0
       0     .06       0      80      .1       0  273.76    .045       0
  296.46      .1       0
#XS Ineff= 2 , 0
          260.74 1436.47
Permanent Ineff=
       F       F
Bank Sta=273.76,296.46
XS Rating Curve= 0 ,0
Exp/Cntr(USF)=0,0
Exp/Cntr=0.3,0.1

Type RM Length L Ch R = 1 ,2045    ,177.6,177.2,176.8
XS GIS Cut Line= 4
1992087.89451971220879.9361961911992303.92726025 220862.55425155
1992440.49968242220822.8240923711992567.13956481220758.262583705
#Sta/Elev= 30
       0  1606.2     8.8 1603.25    31.9  1587.1    71.4 1552.49     101 1519.22
   104.3 1514.02   114.1 1492.04   117.4  1488.2   150.3  1461.9   163.5 1449.79
   176.7 1440.55   196.4 1430.55   233.2 1429.12   250.3 1422.63   277.7 1421.91
   287.9 1418.96   300.9 1418.33  305.751416.453   318.7 1414.38   335.7 1414.84
  340.25 1416.45   342.6 1419.11   349.4    1435     359 1446.71   366.4  1457.5
   385.9 1472.13   403.9 1483.46   422.9 1501.51   433.4 1506.59   501.1 1528.64
#Mann= 4 ,-1 , 0
       0     .04       0     130      .1       0  305.75    .045       0
  340.25     .12       0
Bank Sta=305.75,340.25
XS Rating Curve= 0 ,0
Exp/Cntr(USF)=0,0
Exp/Cntr=0.3,0.1

Type RM Length L Ch R = 1 ,1867    ,200.3,199.6,198.4
XS GIS Cut Line= 4
1992172.32110797221073.6207221881992378.42130871221023.958023214
1992510.02746099220986.7109989841992661.49869286220949.463974754
#Sta/Elev= 30
       0  1582.9     9.9 1582.09    20.1 1577.38    47.1 1558.15    67.3 1541.32
    80.8 1532.62   107.8 1508.59   141.6 1482.52   158.4 1464.54   178.7 1448.85
   193.7 1432.14   202.3 1424.71     209 1422.83   243.1 1421.08   246.5 1419.97
  254.691413.934   286.2 1412.67  309.931413.931   328.4 1417.53   352.2 1431.48
   355.6 1435.39   362.3 1448.94   365.7 1452.51   378.1 1460.07     386 1468.41
   402.5 1480.02   423.1 1488.63     454 1506.09   480.6 1514.84   504.8 1519.39
#Mann= 4 ,-1 , 0
       0     .04       0      50      .1       0  254.69    .045       0
  309.93      .1       0
Bank Sta=254.69,309.93
XS Rating Curve= 0 ,0
Exp/Cntr(USF)=0,0
Exp/Cntr=0.3,0.1

Type RM Length L Ch R = 1 ,1668    ,196.9,197,192.1
XS GIS Cut Line= 4
1992271.64650591221259.8558433391992415.66833294221222.608819109
1992616.80226378221160.5304453921992763.30722575221110.867746418
#Sta/Elev= 30
       0 1575.68    10.1 1567.41      26 1559.12    39.7 1549.47    90.4    1508
   100.5 1497.58   127.7 1477.48   137.8 1465.76   165.1 1440.15   175.4 1425.98
   178.9  1422.9   185.8 1419.32   213.2 1419.21   216.7 1417.93   223.4 1412.54
   230.4 1410.82   262.9 1411.97   288.8 1412.36   299.6 1410.56   312.8 1412.74
   319.7 1416.12   336.8 1428.58   340.3 1432.45   349.4 1446.37     354 1451.09
   385.1 1469.15     399 1478.79   423.2 1492.01   457.9  1503.7513.9499 1511.85
#Mann= 4 ,-1 , 0
       0     .04       0      50      .1       0   223.4    .045       0
   262.9      .1       0
Bank Sta=223.4,262.9
XS Rating Curve= 0 ,0
Exp/Cntr(USF)=0,0
Exp/Cntr=0.3,0.1

Type RM Length L Ch R = 1 ,1471    ,285.8,290.8,293.9
XS GIS Cut Line= 4
1992259.23083117221369.1137810811992465.33103191221354.214971389
1992681.36377245221324.4173520051992870.08202855221302.069137466
#Sta/Elev= 30
       0  1573.1    31.1 1574.96      41 1584.25    47.5 1583.32    57.4 1577.49
    83.7 1556.05   119.9 1529.28   149.8 1504.48     166 1489.21   169.3 1483.82
   175.8 1468.13   179.1 1462.68   198.8  1443.7   231.9 1416.59     275 1417.09
   288.2 1409.38   314.7 1412.07   365.1 1409.04   374.3  1408.3   384.3  1409.2
   404.1 1426.72   407.5 1431.35   417.5 1451.72     424 1460.42   463.7 1484.86
   476.9 1494.75   500.1 1504.21   519.8 1509.32   572.7 1515.45 614.753 1517.83
#Mann= 4 ,-1 , 0
       0     .04       0      60      .1       0   365.1    .045       0
   384.3      .1       0
Bank Sta=365.1,384.3
XS Rating Curve= 0 ,0
Exp/Cntr(USF)=0,0
Exp/Cntr=0.3,0.1

Type RM Length L Ch R = 1 ,1180    ,319.7,316.5,315.7
XS GIS Cut Line= 4
1992224.46694189221565.2814420261992442.98281737221597.562196359
1992790.62171019   221614.9441411992971.89056144221622.393545846
#Sta/Elev= 30
       0 1598.92    10.1 1589.08    33.3 1559.79    76.4 1562.22    89.7 1560.35
   132.8 1526.94   175.9 1498.13   209.1 1477.18   225.6  1470.3   238.8 1460.91
   261.8 1447.88   268.3 1441.83   272.4 1434.54   278.2 1420.72   284.8 1413.95
   291.1 1412.48   333.1 1412.25   347.2 1409.68   396.5 1408.01   409.6 1405.81
   432.6 1407.77   455.6 1407.02   475.3 1405.81   478.3 1407.01   481.9 1411.81
   508.1  1459.7   527.9 1483.82   560.7 1498.36   591.6 1505.63750.3824 1512.69
#Mann= 7 ,-1 , 0
       0     .04       0     200      .1       0  390.89    .025       0
   455.6    .045       0   478.3    .025       0  490.89     .12       0
  688.96      .1       0
#XS Ineff= 2 , 0
          327.44 1423.73
Permanent Ineff=
       F       F
Bank Sta=455.6,478.3
XS Rating Curve= 0 ,0
Exp/Cntr(USF)=0,0
Exp/Cntr=0.3,0.1

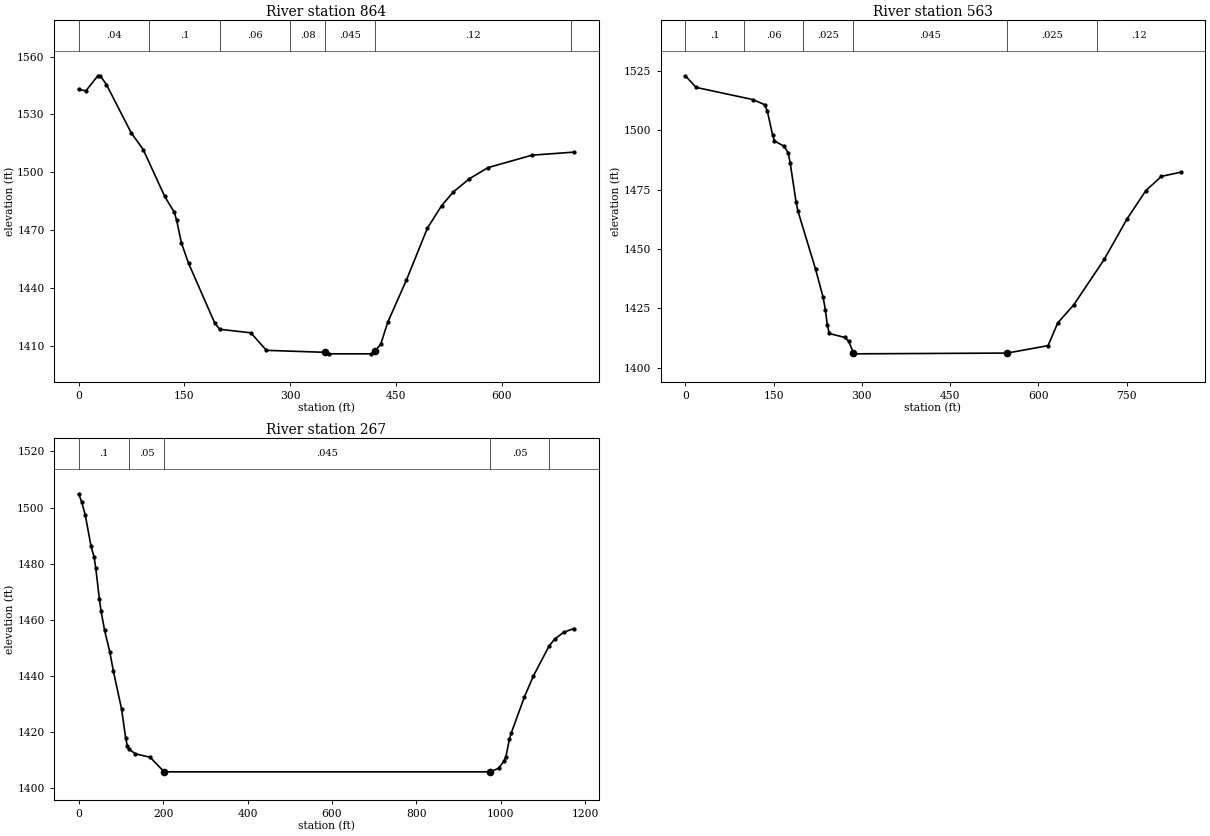
Type RM Length L Ch R = 1 ,864     ,300.2,300.2,300.2
XS GIS Cut Line= 4
1992224.46694189221838.4262863811992428.08400768221890.572120304
1992743.44214616221932.7854144311992917.26159257221920.369739688
#Sta/Elev= 30
       0 1543.01    10.3 1542.24    27.3 1550.05    30.7 1550.04    39.5 1545.45
    74.5 1520.51    91.6  1511.8   122.1 1487.47   135.6  1479.3     139 1475.13
   145.8 1463.31     156 1452.72   193.2 1421.67     200 1418.56   244.3  1416.7
   266.4 1407.62   348.9 1406.61   355.8 1405.81   415.4 1405.81   420.51407.306
   428.6  1410.9   438.5 1422.24     465 1444.14   494.8 1471.08   514.7 1482.58
   531.2 1489.69   554.2 1496.62   580.5 1502.39     643 1508.86702.6215 1510.45
#Mann= 7 ,-1 , 0
       0     .04       0     100      .1       0     200     .06       0
  300.19     .08       0   348.9    .045       0   420.5     .12       0
  698.36      .1       0
Bank Sta=348.9,420.5
XS Rating Curve= 0 ,0
Exp/Cntr(USF)=0,0
Exp/Cntr=0.3,0.1

Type RM Length L Ch R = 1 ,563     ,295.5,295.5,295.5
XS GIS Cut Line= 4
1992127.62467889222156.2675598121992363.52249902222195.997718991
1992783.17230534222228.2784733241992952.02548185 222161.23382971
#Sta/Elev= 30
       0 1523.05    18.5 1518.14     115 1513.01     135 1510.85   139.5 1508.06
   148.3 1498.22   151.6 1495.59   168.2 1493.29   174.9 1490.49   178.2  1486.4
   188.2 1469.94   191.5 1465.96   221.5 1441.42   234.3 1429.59   238.1 1424.29
   241.4 1417.96   244.7 1414.39   270.6 1412.76   277.6  1411.2  285.841406.132
   287.5 1405.81  546.891406.132   616.5 1409.26     633 1418.87   660.1 1426.45
   712.2 1445.75   751.1 1462.87   782.8 1474.67   809.2 1480.65841.7863 1482.38
#Mann= 6 ,-1 , 0
       0      .1       0     100     .06       0     200    .025       0
  285.84    .045       0  546.89    .025       0  700.11     .12       0
Bank Sta=285.84,546.89
XS Rating Curve= 0 ,0
Exp/Cntr(USF)=0,0
Exp/Cntr=0.3,0.1

Type RM Length L Ch R = 1 ,267     ,,,
XS GIS Cut Line= 4
1992176.38537945222205.135873535 1992407.1841375222503.542348586
1992759.21052603222512.8675509321993043.62919757222172.497665327
#Sta/Elev= 30
       0 1504.91     7.5 1501.89    15.8 1497.29    29.3 1486.29    36.6 1482.36
    40.7 1478.29      49 1467.55    53.1 1463.11    61.4  1456.3    73.9 1448.48
    82.2 1441.76   101.8 1428.12   111.2 1418.02   115.4 1415.01   119.5 1413.87
   134.5 1412.23   169.3 1411.01   202.5 1405.81   974.1 1405.81   994.4 1407.06
  1007.2 1409.66  1011.5 1411.06  1020.1 1417.47  1024.3 1419.61  1055.6 1432.51
  1076.5  1439.9  1113.8 1450.61  1126.9 1453.08  1148.3 1455.541172.956 1456.88
#Mann= 5 ,-1 , 0
       0      .1       0   119.5     .05       0   202.5    .045       0
   974.1     .05       0  1113.8      .1       0
Bank Sta=202.5,974.1
XS Rating Curve= 0 ,0
Exp/Cntr(USF)=0,0
Exp/Cntr=0.3,0.1
LCMann Table=0

Chan Stop Cuts=-1
Use User Specified Reach Order=0
Composite Channel Slope=5